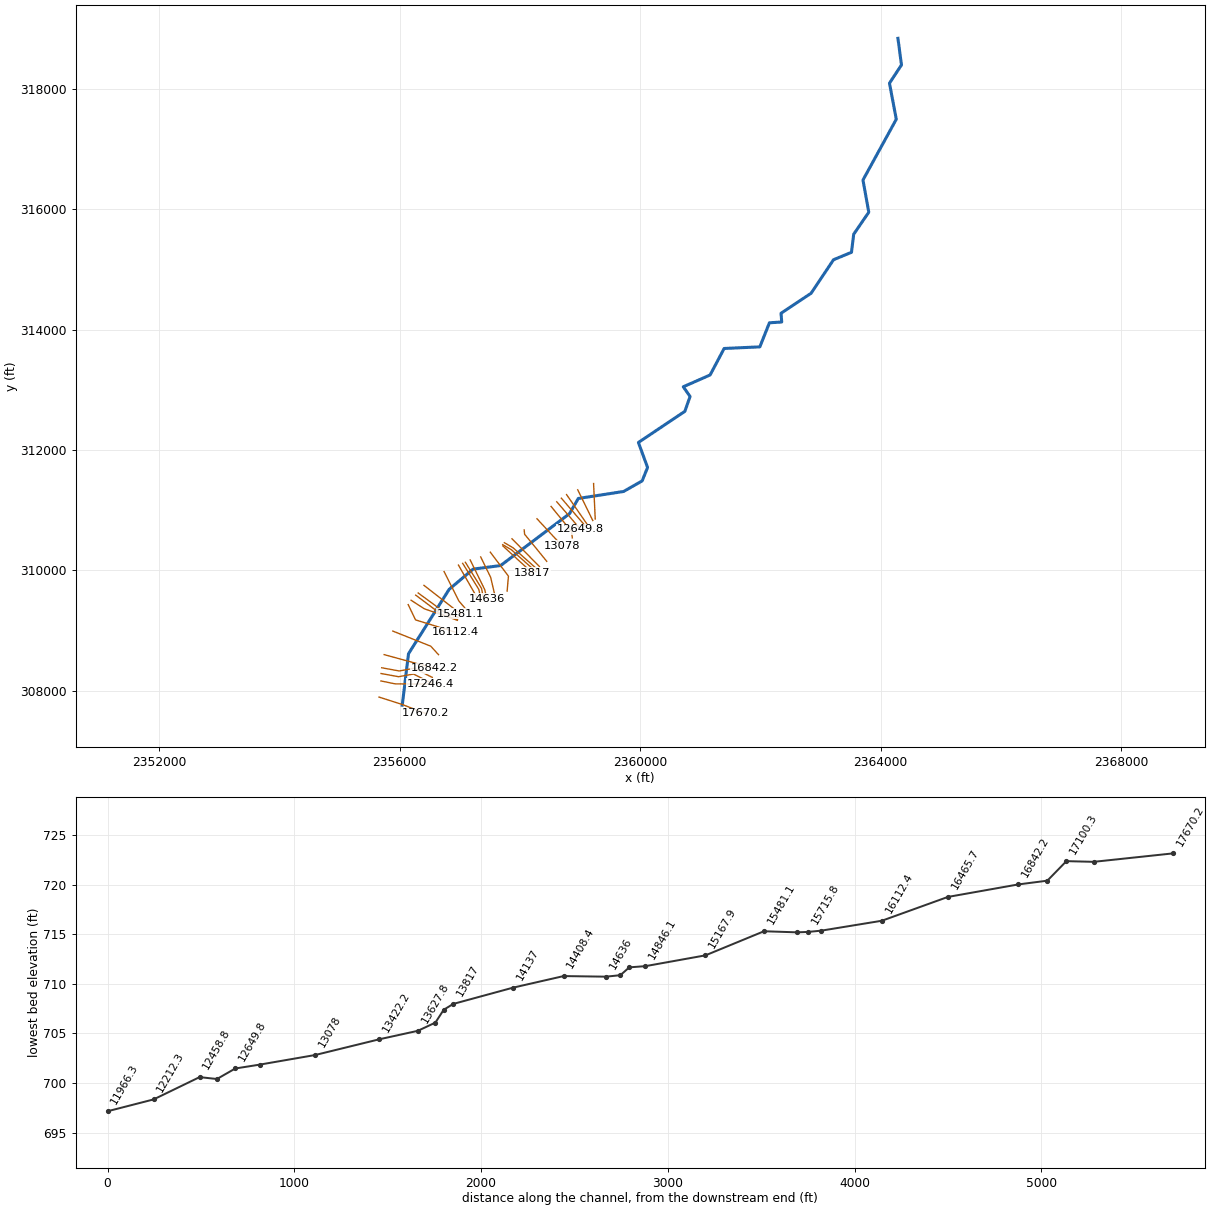
--- MILLCREEK1.prj (project) ---

Proj Title=MILLCREEK1
Current Plan=p01
Default Exp/Contr=0,0
English Units
Geom File=g01
Flow File=f01
Plan File=p01
BEGIN DESCRIPTION:
END DESCRIPTION:
DSS Export Rating Curves= 0
DSS Export Rating Curve Sorted= 0
DSS Export Volume Flow Curves= 0
DXF OffsetX= 0
DXF OffsetY= 0
DXF ScaleX= 0
DXF ScaleY= 0

--- MILLCREEK1.p01 (plan) ---

Plan Title=Floodplain
Program Version=4.00
Geom File=g01
Flow File=f01
K Sum by GR=0
Std Step Tol=0.01
Critical Tol=0.01
Num of Std Step Trials=20
Max Error Tol=0.3
Flow Tol Ratio=0.001
Split Flow NTrial=30
Split Flow Tol=0.02
Split Flow Ratio=0.02
Log Output Level=0
Friction Slope Method=1
Unsteady Friction Slope Method=2
Unsteady Bridges Friction Slope Method=1
Global Log Level=0
CheckData=False
Run HTab=0
Run UNet=0
Run PostProcess=0
UNET Theta=0
UNET Theta Warmup=0
UNET ZTol=0
UNET ZSATol=0
UNET MxIter=0
UNET MaxInSteps=0
UNET DtIC=0
UNET DtMin=0
UNET MaxCRTS=0
UNET WFStab=0
UNET SFStab=0
UNET WFX=0
UNET SFX=0
UNET DSS MLevel=0
UNET DZMax Abort=0
UNET Convert EG Bridges=0
UNET Use Existing IB Tables=0
UNET Froude Limit=0
UNET Froude Power=0
Write IC File=0
Echo Input=False
Echo Output=False
Write Detailed=0

--- MILLCREEK1.f01 (steady flow) ---

Flow Title=NFF Regression Equation
Program Version=4.10
Number of Profiles= 1
Profile Names=P100yr
River Rch & RM=MILLCREEK1,Main            ,17670.2
 541.236
River Rch & RM=MILLCREEK1,Main            ,16112.4
600.4815
River Rch & RM=MILLCREEK1,Main            ,15787.6
 681.103
River Rch & RM=MILLCREEK1,Main            ,14712.1
753.3466
River Rch & RM=MILLCREEK1,Main            ,13817
  813.59
River Rch & RM=MILLCREEK1,Main            ,12212.3
887.8899
River Rch & RM=MILLCREEK1,Main            ,11052.9
926.2821
River Rch & RM=MILLCREEK1,Main            ,7933.3
1001.352
River Rch & RM=MILLCREEK1,Main            ,7362.8
1183.885
River Rch & RM=MILLCREEK1,Main            ,211.4
1292.034
Boundary for River Rch & Prof#=MILLCREEK1,Main            , 1
Up Type= 0
Dn Type= 1
Dn Known WS=660.5
DSS Import GetInterval= 0
DSS Import GetPeak= 0
DSS Import FillOption= 0

--- MILLCREEK1.g01 (geometry) ---

Geom Title=USGS 10m DEM
Program Version=5.03

River Reach=MILLCREEK1      ,Main
Reach XY= 30
     2356043.593      307760.166      2356147.76      308614.333
     2356823.392      309684.127     2357222.446      310020.895
     2357678.614      310078.987     2358826.091       310942.51
     2358970.528      311194.022     2359724.149      311310.513
      2360033.24      311486.276     2360123.132      311709.647
     2359970.676      312124.749     2360743.246       312642.11
     2360829.825      312888.502     2360717.204      313050.096
     2361163.384      313246.277     2361396.522      313686.667
     2361989.774      313713.291     2362149.578      314113.298
     2362353.653      314126.522      2362342.72      314272.152
     2362842.204      314603.916     2363215.468      315161.207
     2363514.079      315284.471     2363550.537      315584.819
     2363801.569      315950.481     2363704.955      316485.377
     2364259.121      317495.272      2364145.58      318095.012
      2364345.24       318397.38     2364286.649      318840.027

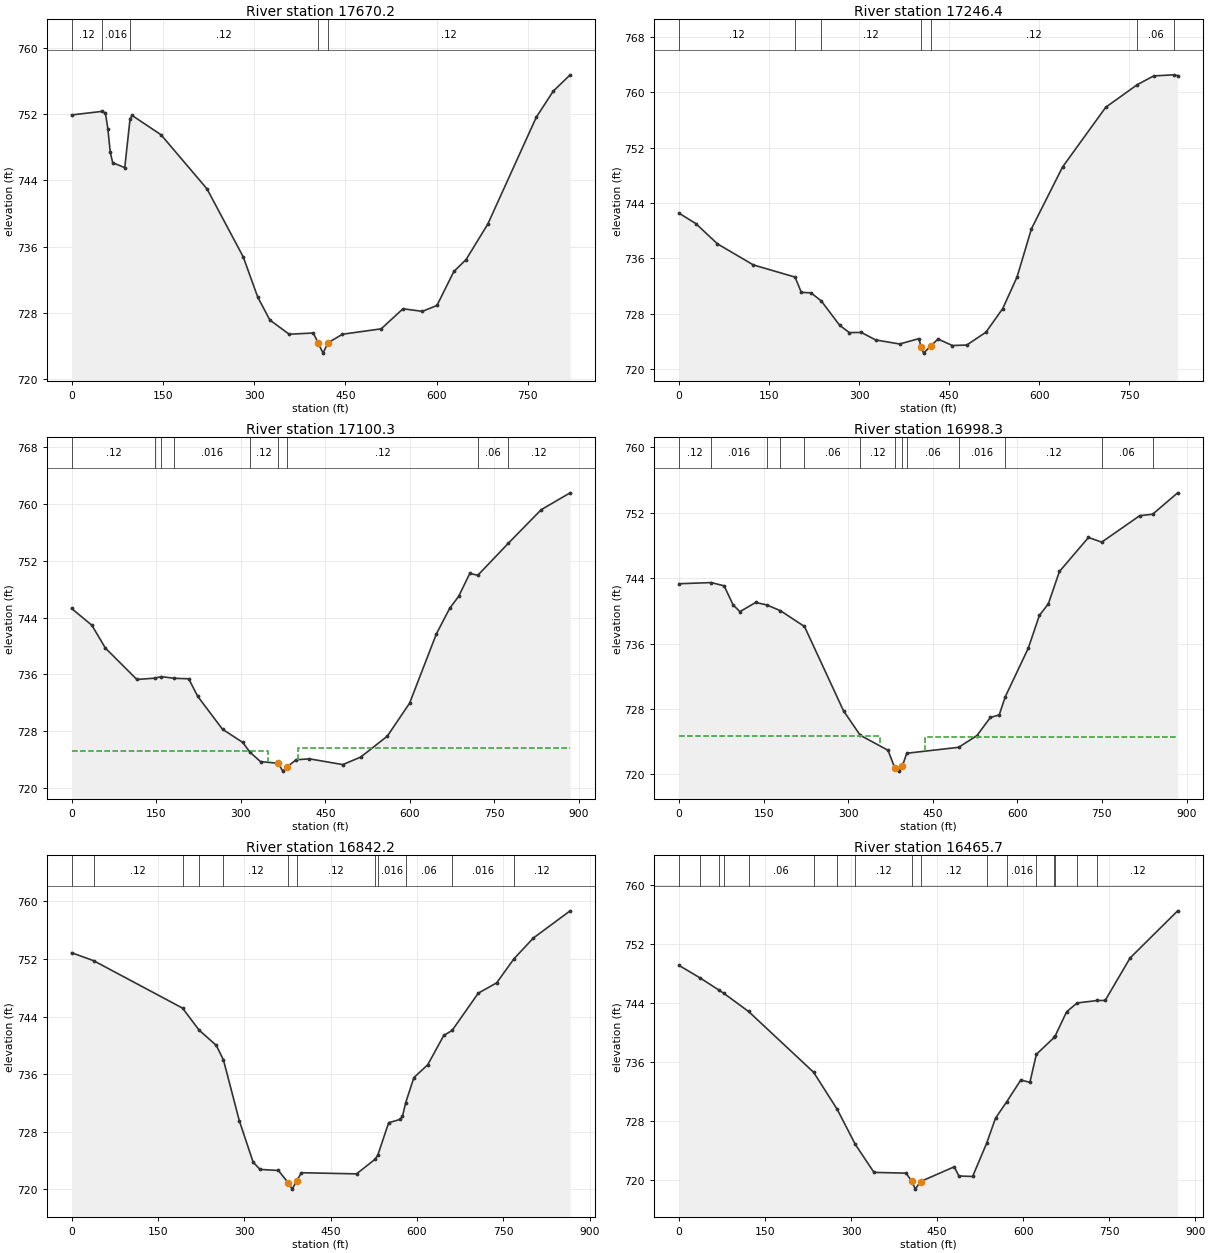
Type RM Length L Ch R = 1 ,17670.2 ,411.5,423.8,396.7
XS GIS Cut Line= 3
      2355656.75      307894.454     2356046.641       307769.69
     2356429.887      307623.285
#Sta/Elev= 30
       0  751.89   50.19752.3196    55.6  752.12    59.6  750.23    63.6  747.36
    67.6  746.13    87.4  745.53   96.15  751.44    99.4  751.83     147   749.5
   222.6  742.97   282.2  734.76     306  729.91   325.9  727.15   357.7  725.43
   397.4  725.58   405.4  724.36   413.4  723.15   421.3  724.38   445.2  725.43
   508.9  726.08   544.8   728.5   576.7  728.19   600.6   728.9   628.4     733
   648.4  734.43   684.2  738.72   763.9  751.61   791.7  754.75   819.6  756.73
#Mann= 5 ,-1 , 0
       0     .12       0   50.19    .016       0   96.15     .12       0
   405.4    .045       0   421.3     .12       0
Bank Sta=405.4,421.3
XS Rating Curve= 0 ,0
Exp/Cntr=0.3,0.1

Type RM Length L Ch R = 1 ,17246.4 ,141.4,146.1,158.2
XS GIS Cut Line= 3
     2355689.243      308161.982     2355927.958      308113.154
     2356514.981      308110.984
#Sta/Elev= 30
       0  742.53      28  741.02    63.9   738.1   123.8  735.05  193.18733.2932
   203.7  731.08   219.7  731.02  236.93729.8416   267.6  726.32   283.6  725.27
   303.6  725.29   327.5  724.21   367.4  723.62   399.4  724.39   403.4  723.18
   407.4   722.3   419.4  723.34   431.4  724.34   455.3   723.4   479.3  723.47
   511.2  725.32   539.2  728.74   563.1  733.31   587.1  740.28     639  749.22
   710.9  757.85  763.43761.1131   790.8  762.38   824.2 762.535   830.7  762.43
#Mann= 7 ,-1 , 0
       0     .12       0  193.18    .016       0  236.93     .12       0
   403.4    .045       0   419.4     .12       0  763.43     .06       0
   824.2     .12       0
Bank Sta=403.4,419.4
XS Rating Curve= 0 ,0
Exp/Cntr=0.3,0.1

Type RM Length L Ch R = 1 ,17100.3 ,101.9,102.1,102.1
XS GIS Cut Line= 4
     2355691.413       308285.68     2355982.212      308232.512
     2356230.693         308277.     2356531.257      308126.175
#Sta/Elev= 30
       0  745.29      36  742.92    59.9  739.71   115.8  735.28   148.3735.4762
   158.9735.6865  182.25735.4478   207.7  735.38   223.7  732.91   267.7  728.27
   303.5  726.42  316.58725.0208   335.1  723.71   366.6  723.48   374.5  722.37
   382.4  722.97   398.2  723.97   421.8   724.1     481  723.29   512.6  724.34
   559.9  727.29   599.5  731.94     647   741.7   670.7  745.32   686.5  746.99
   706.3  750.23  720.49749.9611  774.33754.4492   832.9   759.2   884.3  761.58
#Mann= 9 ,-1 , 0
       0     .12       0   148.3     .06       0   158.9     .12       0
  182.25    .016       0  316.58     .12       0   366.6    .045       0
   382.4     .12       0  720.49     .06       0  774.33     .12       0
#XS Ineff= 2 , 0
          347.78  725.15  401.44          725.57
Permanent Ineff=
       F       F
Bank Sta=366.6,382.4
XS Rating Curve= 0 ,0
Exp/Cntr=0.3,0.1

Type RM Length L Ch R = 1 ,16998.3 ,166.3,156.1,145.9
XS GIS Cut Line= 4
     2355702.264      308381.167     2355993.062      308327.998
     2356241.543      308372.486     2356542.108      308221.661
#Sta/Elev= 30
       0  743.32   57.26743.4634    79.9  743.06    95.9  740.72   107.9  739.91
   135.8  741.03   155.5740.7307  179.84740.0177  222.41738.0903   291.6  727.78
  321.26724.7894   370.6  722.95   382.4  720.82   390.3   720.4  395.88 720.997
   403.8722.5875  495.79 723.312   528.3  724.75     552  726.96   567.8  727.28
   578.5729.4954   619.3  735.43     639  739.44   654.9  740.86   674.6  744.82
   726.1  748.98   749.6748.4105   817.1  751.65  839.92751.8232   884.3  754.44
#Mann= 13 ,-1 , 0
       0     .12       0   57.26    .016       0   155.5     .06       0
  179.84    .016       0  222.41     .06       0  321.26     .12       0
   382.4    .045       0  395.88     .12       0   403.8     .06       0
  495.79    .016       0   578.5     .12       0   749.6     .06       0
  839.92     .12       0
#XS Ineff= 2 , 0
          356.04  724.73  436.53          724.61
Permanent Ineff=
       F       F
Bank Sta=382.4,395.88
XS Rating Curve= 0 ,0
Exp/Cntr=0.3,0.1

Type RM Length L Ch R = 1 ,16842.2 ,379,376.5,373.9
XS GIS Cut Line= 2
     2355743.496      308599.265        2356579.      308371.401
#Sta/Elev= 30
       0  752.87   38.13751.7654  192.72745.1732  221.41 742.122   251.4  739.99
  263.82737.9661   291.3  729.53   315.3  723.78   327.2  722.76   359.2  722.61
   376.2  720.91   383.1  720.02   391.2  721.18   399.1   722.3   494.9  722.14
  526.96724.1568  531.77724.7177   550.7  729.24   570.7  729.71   574.7  730.12
   580.4732.0535   594.6  735.52   618.6   737.3   646.5  741.38  660.95742.0654
   706.4  747.25   738.3  748.68  768.42752.0287   802.2  754.92     866  758.69
#Mann= 12 ,-1 , 0
       0    .016       0   38.13     .12       0  192.72     .06       0
  221.41    .016       0  263.82     .12       0   376.2    .045       0
   391.2     .12       0  526.96     .06       0  531.77    .016       0
   580.4     .06       0  660.95    .016       0  768.42     .12       0
Bank Sta=376.2,391.2
XS Rating Curve= 0 ,0
Exp/Cntr=0.3,0.1

Type RM Length L Ch R = 1 ,16465.7 ,351.5,353.4,355.5
XS GIS Cut Line= 3
     2355886.726      308990.976     2356518.236      308739.239
     2356646.274      308599.265
#Sta/Elev= 30
       0  749.11   36.73747.4117   69.33745.7735   77.99745.3308  121.08742.8687
  234.55734.6214  275.78729.5862  307.35724.8237   339.9  721.03   395.9  720.93
  405.99719.7988   411.9  718.76  421.03719.7879   479.9  721.79   487.9  720.54
   511.9  720.48   536.2 724.952   551.9   728.4  571.49730.6277   595.9  733.56
   611.8  733.25  623.06737.0534  654.63739.3767  655.55739.4894   675.8  742.82
  694.09744.0174  729.65744.3542   743.1  744.36   786.5  750.12   869.5  756.52
#Mann= 17 ,-1 , 0
       0     .06       0   36.73    .016       0   69.33     .06       0
   77.99    .016       0  121.08     .06       0  234.55    .016       0
  275.78     .06       0  307.35     .12       0  405.99    .045       0
  421.03     .12       0   536.2     .06       0  571.49    .016       0
  623.06     .12       0  654.63     .06       0  655.55     .12       0
  694.09     .08       0  729.65     .12       0
Bank Sta=405.99,421.03
XS Rating Curve= 0 ,0
Exp/Cntr=0.3,0.1

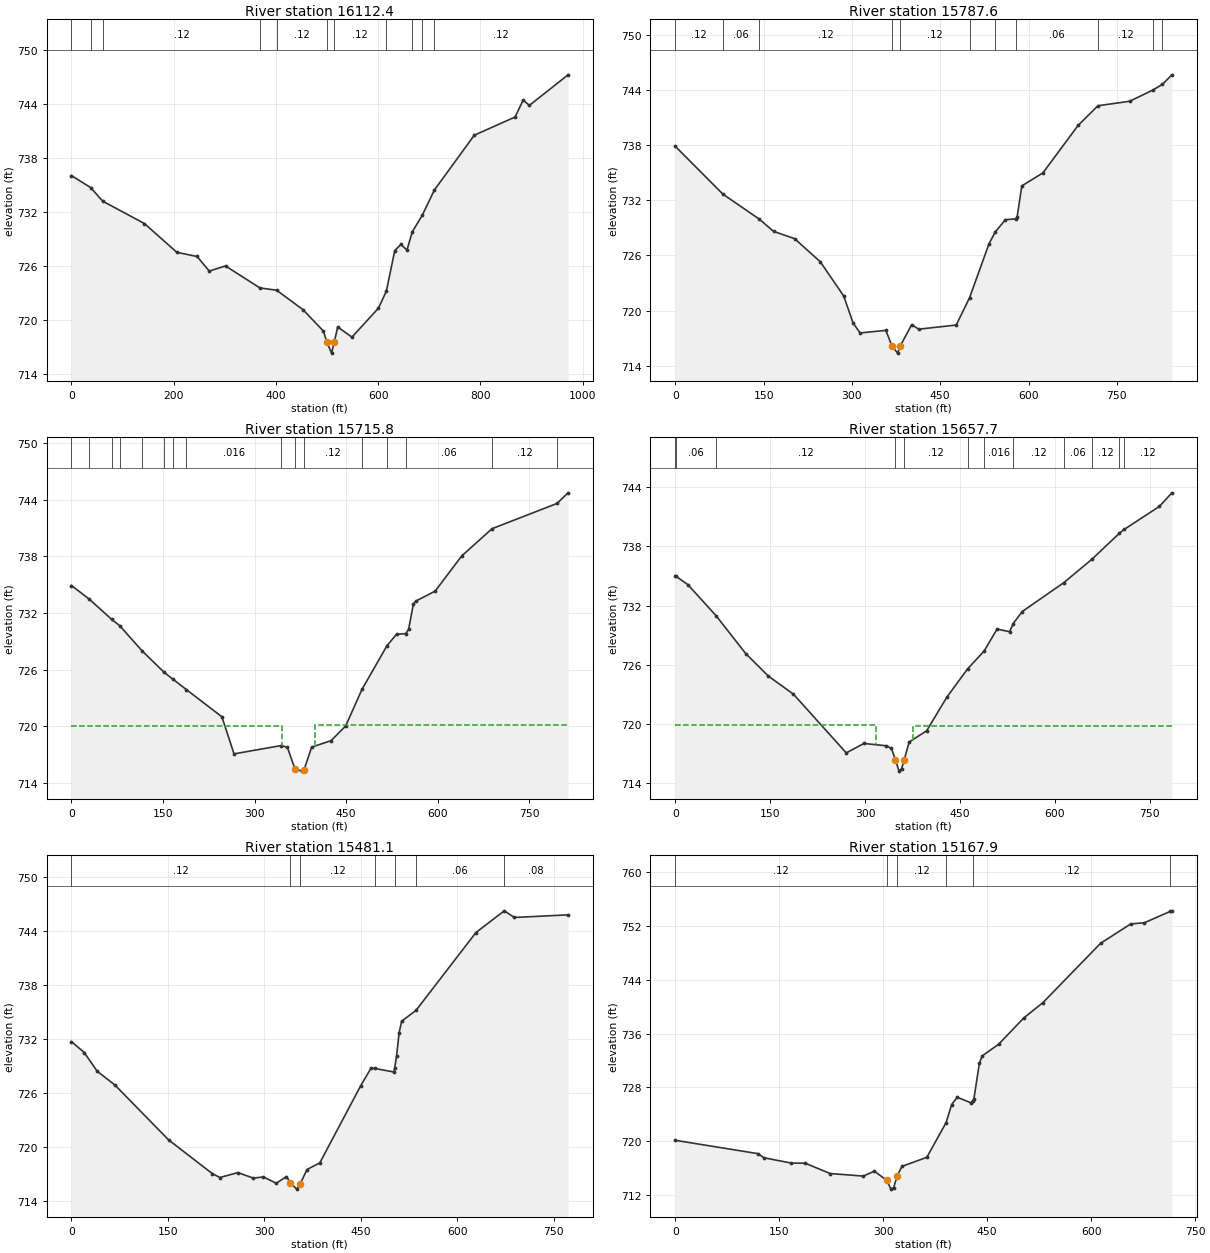
Type RM Length L Ch R = 1 ,16112.4 ,322.4,324.8,277.6
XS GIS Cut Line= 3
     2356142.802      309430.429      2356264.33      309176.522
     2356924.052      308973.614
#Sta/Elev= 30
       0  736.09   37.44734.7606   61.21733.2435   142.7  730.76   206.2  727.56
   245.8   727.1   269.6  725.48   301.4  726.05  368.83723.6017  401.33723.3561
     453  721.19     493  718.81  499.73717.5784   508.9  716.36  514.15717.5869
   520.9  719.27   548.8  718.14   600.7  721.36  616.16723.2562   632.6  727.76
   644.6  728.44   656.5  727.82     667729.8613  686.19731.6588  710.13734.4892
   788.2  740.58     868   742.6   883.9  744.49   895.9  743.89   971.7  747.29
#Mann= 11 ,-1 , 0
       0     .12       0   37.44    .016       0   61.21     .12       0
  368.83    .016       0  401.33     .12       0  499.73    .045       0
  514.15     .12       0  616.16    .016       0     667     .12       0
  686.19     .06       0  710.13     .12       0
Bank Sta=499.73,514.15
XS Rating Curve= 0 ,0
Exp/Cntr=0.3,0.1

Type RM Length L Ch R = 1 ,15787.6 ,81.3,71.8,68.8
XS GIS Cut Line= 3
     2356190.545      309503.128     2356410.814      309360.984
     2356959.859      309170.012
#Sta/Elev= 30
       0  737.89   80.95732.6747  142.65729.9589   166.8  728.63   202.6  727.83
   246.3  725.31     286  721.59     302  718.64   313.9  717.56   357.7  717.84
  367.81716.1592   377.6  715.36   382.5  716.19   401.5  718.46   413.4  717.97
   477.2  718.42  499.98  721.42   532.9  727.28  543.71728.5866   560.8   729.9
  578.77729.9839   580.7  730.23   588.6  733.58   624.5     735   684.2  740.17
  717.95742.3134   771.8   742.8   811.3744.0255  827.37744.6393   843.5  745.68
#Mann= 11 ,-1 , 0
       0     .12       0   80.95     .06       0  142.65     .12       0
  367.81    .045       0   382.5     .12       0  499.98     .06       0
  543.71    .016       0  578.77     .06       0  717.95     .12       0
   811.3     .06       0  827.37     .08       0
Bank Sta=367.81,382.5
XS Rating Curve= 0 ,0
Exp/Cntr=0.3,0.1

Type RM Length L Ch R = 1 ,15715.8 ,57.6,58.1,58.1
XS GIS Cut Line= 3
     2356267.585      309587.764     2356684.252      309275.264
     2356962.029      309181.948
#Sta/Elev= 30
       0  734.91   28.98 733.474   66.01731.3135      79730.6537  116.31727.9413
  151.89725.7042  166.62724.9609  188.34723.8762   246.5  720.99   266.4  717.06
  342.94717.9314   353.8  717.77   366.2  715.46   377.7  715.23   381.2  715.38
   393.6  717.77   425.4  718.46   449.3  720.01  476.22723.9148   517.3728.5487
   532.7  729.74  548.01729.8162   552.5  730.26   560.4  732.94   564.4  733.26
   596.1  734.32   639.6  738.05  689.39740.9398  795.76743.6135   813.9  744.74
#Mann= 16 ,-1 , 0
       0     .06       0   28.98    .016       0   66.01     .12       0
      79    .016       0  116.31     .06       0  151.89    .016       0
  166.62     .06       0  188.34    .016       0  342.94     .12       0
   366.2    .045       0   381.2     .12       0  476.22     .06       0
   517.3    .016       0  548.01     .06       0  689.39     .12       0
  795.76     .08       0
#XS Ineff= 2 , 0
          344.69  720.02  398.35          720.07
Permanent Ineff=
       F       F
Bank Sta=366.2,381.2
XS Rating Curve= 0 ,0
Exp/Cntr=0.3,0.1

Type RM Length L Ch R = 1 ,15657.7 ,174.1,176.6,170
XS GIS Cut Line= 3
     2356308.818      309623.571     2356761.292      309292.625
      2356972.88       309216.67
#Sta/Elev= 30
       0  734.99    1.08734.9657    19.9  734.12   64.71 730.949   111.3  727.13
   147.1  724.84   186.9     723   270.4  717.04   298.2     718     334  717.76
   341.9  717.49   348.1716.3406   353.8  715.19   357.8  715.43   361.8  716.28
   369.8  718.14   397.6  719.29   429.4  722.69  462.21725.5656  488.47727.3838
   508.9  729.61   528.8  729.34  534.48730.1755   548.7  731.39  614.65734.3287
  659.06736.7058  702.38739.3362  710.16739.7355   765.7  742.06   785.4  743.44
#Mann= 12 ,-1 , 0
       0    .016       0    1.08     .06       0   64.71     .12       0
   348.1    .045       0   361.8     .12       0  462.21     .06       0
  488.47    .016       0  534.48     .12       0  614.65     .06       0
  659.06     .12       0  702.38     .06       0  710.16     .12       0
#XS Ineff= 2 , 0
          317.03  719.92  375.64          719.76
Permanent Ineff=
       F       F
Bank Sta=348.1,361.8
XS Rating Curve= 0 ,0
Exp/Cntr=0.3,0.1

Type RM Length L Ch R = 1 ,15481.1 ,324.1,313.3,287.3
XS GIS Cut Line= 2
     2356404.986      309750.843     2357014.113      309276.349
#Sta/Elev= 30
       0  731.69    19.9  730.48    39.8  728.42    67.7  726.86   151.2  720.76
   218.9  717.03   230.8  716.59   258.7  717.14   282.6  716.53   298.5  716.65
   318.4  715.95   334.3   716.7  340.42715.9838   350.2   715.3  355.68715.9087
   366.2  717.48   386.1  718.22   449.7   726.8   465.7  728.74  471.99728.7104
   501.5  728.32  502.59728.8078   505.5  730.11   509.4  732.69   513.4  733.97
   535.6735.1665   628.8  743.82  672.85746.2375   688.6   745.5   772.1  745.79
#Mann= 7 ,-1 , 0
       0     .12       0  340.42    .045       0  355.68     .12       0
  471.99    .016       0  502.59     .12       0   535.6     .06       0
  672.85     .08       0
Bank Sta=340.42,355.68
XS Rating Curve= 0 ,0
Exp/Cntr=0.3,0.1

Type RM Length L Ch R = 1 ,15167.9 ,318.3,321.8,319.5
XS GIS Cut Line= 3
      2356739.59      309979.474     2356984.816      309491.193
     2357095.493      309362.069
#Sta/Elev= 30
       0  720.13   119.6  718.14   127.6  717.54   167.5  716.74   187.4  716.72
   223.4  715.19   271.2  714.81   287.2  715.54   305.1  714.18   311.1  712.87
   315.1  713.09   320.1  714.84     327  716.25   362.9   717.6  390.63722.7393
   398.8  725.45   406.8  726.53   426.8   725.7  429.46 726.041   430.7   726.2
   438.7  731.56   442.7  732.67   466.6  734.42   502.5  738.29   530.4   740.6
   613.6  749.42   657.1   752.3   676.9  752.48   714.2754.1695   716.5  754.25
#Mann= 6 ,-1 , 0
       0     .12       0   305.1    .045       0   320.1     .12       0
  390.63    .016       0  429.46     .12       0   714.2     .06       0
Bank Sta=305.1,320.1
XS Rating Curve= 0 ,0
Exp/Cntr=0.3,0.1

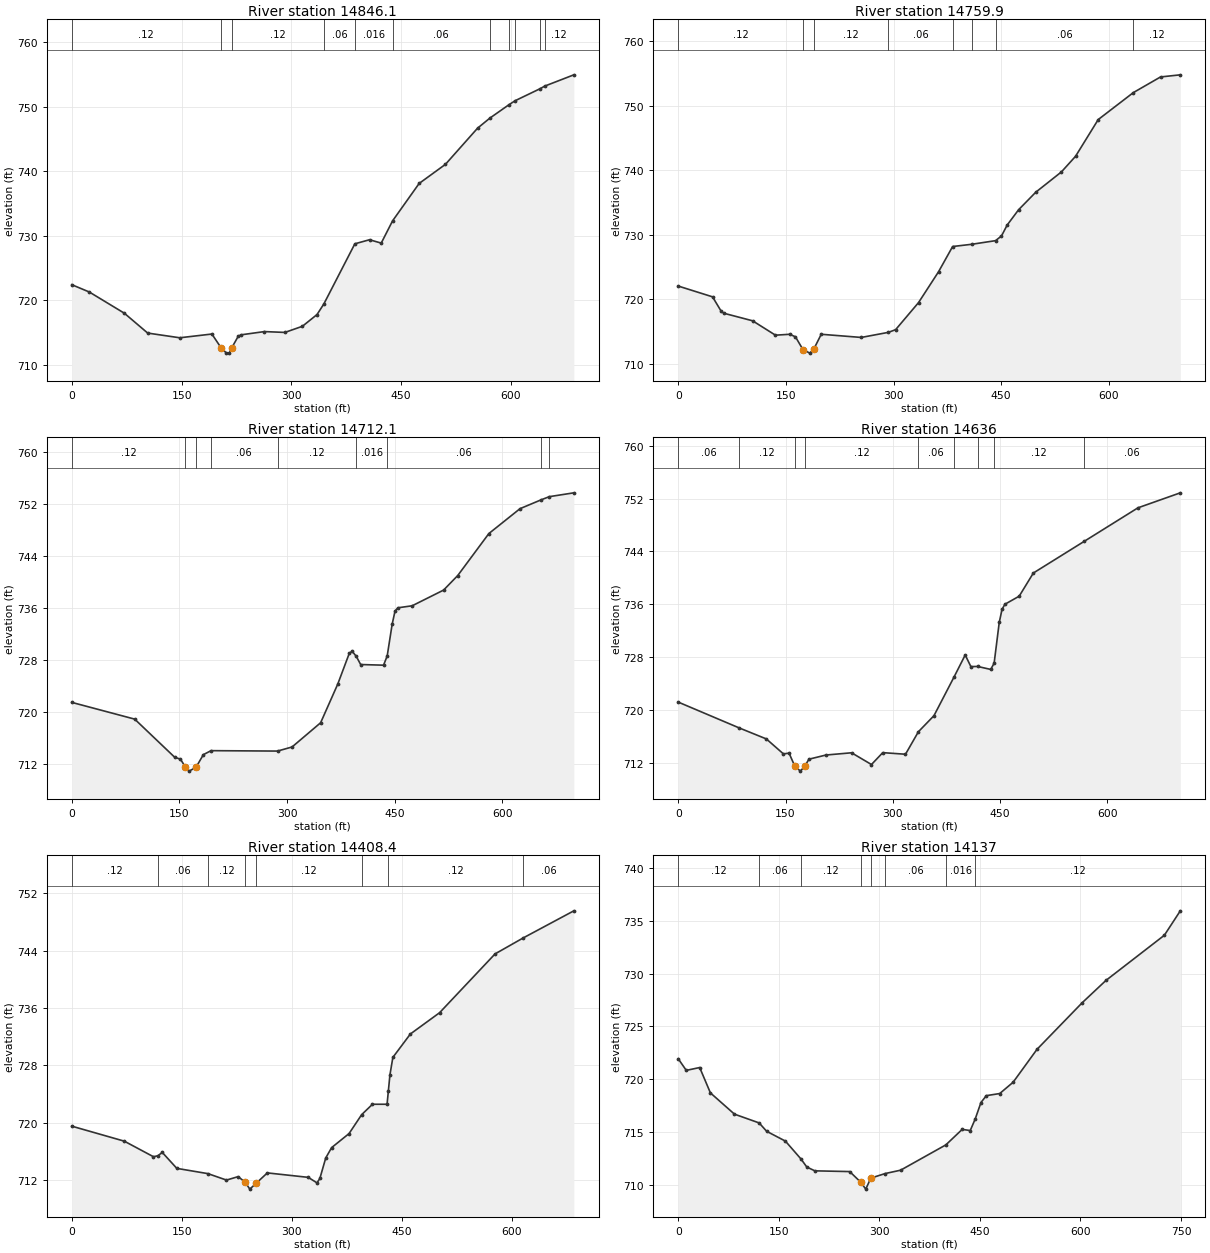
Type RM Length L Ch R = 1 ,14846.1 ,85.5,86.2,85.9
XS GIS Cut Line= 2
     2356978.305      310086.896     2357320.102      309492.278
#Sta/Elev= 30
       0  722.39    23.9  721.26    71.8  717.97   103.7  714.89   147.5  714.16
   191.4  714.74   203.7  712.65   211.3  711.78   215.3  711.82   218.7  712.64
   227.3  714.38   231.3  714.62   263.2  715.12   291.1  714.99     315  715.94
     335  717.76  344.37 719.412  386.68728.7317   406.7  729.36   422.7  728.84
   438.2 732.287   474.5  738.09   510.4  741.05   554.3  746.66  571.26748.2328
  597.14750.2924  605.64750.9178  640.01752.7956  646.03753.1816   685.8  754.93
#Mann= 11 ,-1 , 0
       0     .12       0   203.7    .045       0   218.7     .12       0
  344.37     .06       0  386.68    .016       0   438.2     .06       0
  571.26     .08       0  597.14     .06       0  605.64     .08       0
  640.01     .06       0  646.03     .12       0
Bank Sta=203.7,218.7
XS Rating Curve= 0 ,0
Exp/Cntr=0.3,0.1

Type RM Length L Ch R = 1 ,14759.9 ,47.7,47.7,48.5
XS GIS Cut Line= 3
     2357048.636      310116.232     2357317.374      309682.466
     2357353.938      309496.579
#Sta/Elev= 30
       0  722.05    47.8  720.38    59.8  718.16    63.8  717.83   103.6  716.67
   135.5  714.44   155.5  714.58   163.4  714.18   173.8  712.21   183.4  711.66
   188.8  712.26   199.3  714.58   255.1  714.09  292.98714.8802     303   715.3
   334.9  719.49   362.8  724.27  382.41728.1752  408.79728.5169  442.21 729.082
   450.5  729.81   458.4   731.5   474.4  733.88   498.3  736.59     534  739.73
   553.7  742.15   585.3  747.84  634.25752.0172   672.1  754.44   699.7  754.77
#Mann= 8 ,-1 , 0
       0     .12       0   173.8    .045       0   188.8     .12       0
  292.98     .06       0  382.41     .08       0  408.79    .016       0
  442.21     .06       0  634.25     .12       0
Bank Sta=173.8,188.8
XS Rating Curve= 0 ,0
Exp/Cntr=0.3,0.1

Type RM Length L Ch R = 1 ,14712.1 ,77,76.2,81.7
XS GIS Cut Line= 3
     2357093.124      310134.678     2357361.861      309700.913
     2357398.426      309515.025
#Sta/Elev= 30
       0  721.46    87.7  718.88   143.5     713   151.5  712.71  157.89711.5747
   163.4  710.87  173.07711.4439   183.4  713.41  194.13 714.023  286.72713.9594
     307  714.59   346.8  718.32   370.7  724.28   386.7     729   390.7  729.34
   396.5  728.55   402.6  727.29   434.5  727.19  439.59728.6104   446.5   733.5
   450.5  735.53   454.5  736.03   474.4  736.34   518.2  738.76   537.9     741
   581.3  747.47   624.7   751.3  653.86752.6512  665.52  753.15   699.7  753.74
#Mann= 9 ,-1 , 0
       0     .12       0  157.89    .045       0  173.07     .12       0
  194.13     .06       0  286.72     .12       0   396.5    .016       0
  439.59     .06       0  653.86     .12       0  665.52     .06       0
Bank Sta=157.89,173.07
XS Rating Curve= 0 ,0
Exp/Cntr=0.3,0.1

Type RM Length L Ch R = 1 ,14636   ,228.1,227.6,220.6
XS GIS Cut Line= 3
     2357173.618      310172.616     2357416.674      309676.739
     2357448.141      309530.255
#Sta/Elev= 30
       0  721.18   85.38717.2612   123.2   715.6     147  713.34     155  713.44
   162.9   711.5   170.8  710.72  176.94711.4708   182.8  712.53   206.6  713.16
   242.4   713.5   270.2  711.72     286  713.52   317.8  713.28  335.84716.6857
   357.6  719.12  385.51 724.945   401.3  728.32   409.2  726.56  418.65726.5809
     437  726.13  441.76727.0828   448.9  733.26   452.9  735.27   456.9  736.01
   476.8  737.23   496.6  740.74   567.4745.5154   642.9  750.62   702.1  752.89
#Mann= 9 ,-1 , 0
       0     .06       0   85.38     .12       0   162.9    .045       0
  176.94     .12       0  335.84     .06       0  385.51     .08       0
  418.65    .016       0  441.76     .12       0   567.4     .06       0
Bank Sta=162.9,176.94
XS Rating Curve= 0 ,0
Exp/Cntr=0.3,0.1

Type RM Length L Ch R = 1 ,14408.4 ,266.5,271.4,275.6
XS GIS Cut Line= 3
     2357348.314      310222.529      2357514.33      309882.903
     2357583.774      309584.509
#Sta/Elev= 30
       0  719.55    71.6  717.46   111.4  715.29   117.3 715.428   123.4  715.89
   143.2  713.67  185.64 712.937   210.9  712.04   226.8  712.52   236.4  711.74
   242.7  710.78   251.4   711.6   266.6  713.04   322.3  712.42   334.3  711.65
   338.2  712.27   346.2  715.12   354.2  716.56     378  718.52  395.17 721.154
   409.9   722.6   429.8   722.6  431.53724.4142   433.7  726.69   437.7  729.13
   461.6  732.39   501.4  735.35     577  743.54  615.15745.7527   684.4  749.54
#Mann= 8 ,-1 , 0
       0     .12       0   117.3     .06       0  185.64     .12       0
   236.4    .045       0   251.4     .12       0  395.17    .016       0
  431.53     .12       0  615.15     .06       0
Bank Sta=236.4,251.4
XS Rating Curve= 0 ,0
Exp/Cntr=0.3,0.1

Type RM Length L Ch R = 1 ,14137   ,314.3,320,321.9
XS GIS Cut Line= 3
     2357507.819      310301.739     2357809.469      309903.519
     2357787.767      309655.038
#Sta/Elev= 30
       0  721.94      12  720.84      32  721.11      48  718.71    83.9   716.7
  120.72715.8705   131.9  715.08   159.9  714.15  183.19712.4549   191.8   711.7
   203.8  711.34   255.8  711.27   272.2  710.27   279.8  709.61   287.2  710.65
  308.84711.0857   331.7   711.4  399.25713.7952   423.6  715.26   435.6  715.15
  443.04716.2452   451.6   717.8   459.6  718.45   479.6  718.65   499.6  719.72
   535.2  722.83   602.5  727.23   638.1  729.35   725.2  733.62     749  735.93
#Mann= 8 ,-1 , 0
       0     .12       0  120.72     .06       0  183.19     .12       0
   272.2    .045       0   287.2     .12       0  308.84     .06       0
  399.25    .016       0  443.04     .12       0
Bank Sta=272.2,287.2
XS Rating Curve= 0 ,0
Exp/Cntr=0.3,0.1

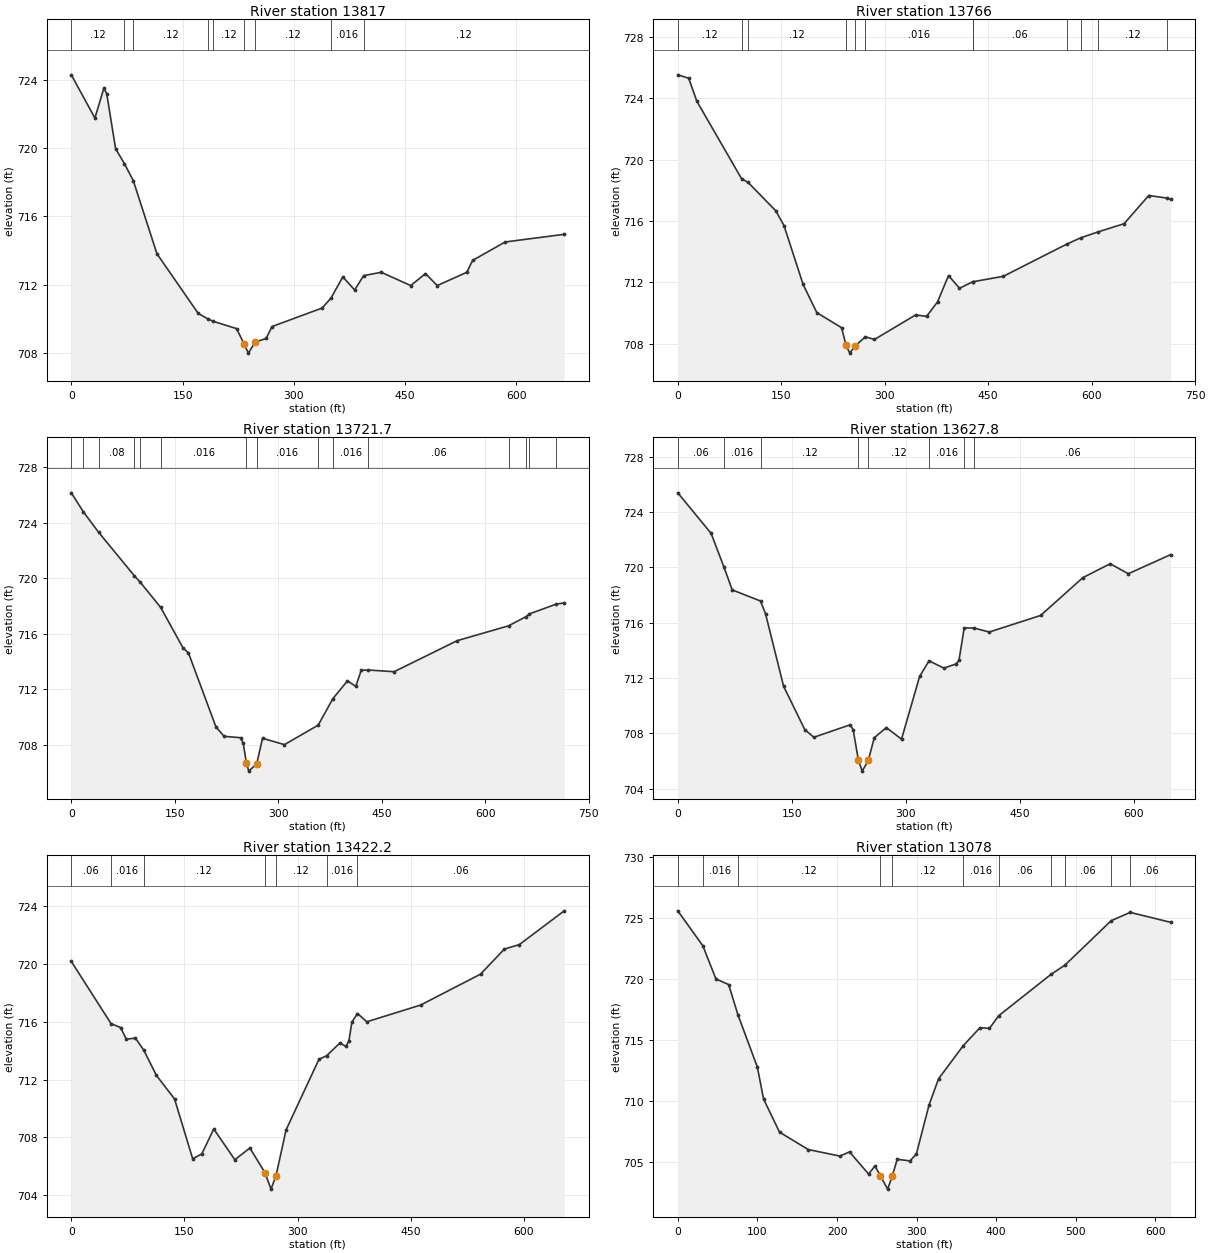
Type RM Length L Ch R = 1 ,13817   ,50.4,50.9,51.3
XS GIS Cut Line= 2
     2357717.238      310404.821     2358207.689      309956.687
#Sta/Elev= 30
       0  724.32    31.8  721.78    43.8  723.52    47.7  723.22    59.7  719.98
   71.67719.0954    83.5  718.11   115.4  713.81   171.1   710.3  183.93709.9837
  190.75709.8456   222.8  709.41   232.8  708.51   238.7  707.97   247.8  708.62
   262.6  708.83   270.5  709.53   338.1  710.62  350.11711.2109     366  712.45
   381.9  711.68  394.03 712.522   417.7  712.72   457.5  711.94   477.4  712.64
   493.3  711.94   533.1  712.72     541  713.42   584.8   714.5   664.4  714.95
#Mann= 9 ,-1 , 0
       0     .12       0   71.67     .06       0    83.5     .12       0
  183.93     .06       0  190.75     .12       0   232.8    .045       0
   247.8     .12       0  350.11    .016       0  394.03     .12       0
Bank Sta=232.8,247.8
XS Rating Curve= 0 ,0
Exp/Cntr=0.3,0.1

Type RM Length L Ch R = 1 ,13766   ,44.4,44.4,44.3
XS GIS Cut Line= 3
     2357713.983      310426.522     2357857.212      310342.972
     2358267.368      309978.389
#Sta/Elev= 30
       0  725.53    15.8  725.31    27.6  723.81   92.58718.7466  101.77718.5222
   142.1  716.66     154   715.7   181.7  711.86   201.6  710.02   237.4  709.04
  243.93707.9047   249.3  707.38   257.3  707.85  271.97708.4485   285.1  708.27
   344.8  709.87   360.7  709.78   376.6  710.72   392.5  712.44   408.4  711.61
   427.9 712.043  428.52  712.04     472  712.39  563.56714.4806  583.88714.8961
  608.83715.2789     647  715.82   682.8  717.66  709.29717.4896   714.6  717.41
#Mann= 12 ,-1 , 0
       0     .12       0   92.58     .08       0  101.77     .12       0
  243.93    .045       0   257.3     .12       0  271.97    .016       0
   427.9     .12       0  428.52     .06       0  563.56     .08       0
  583.88     .06       0  608.83     .12       0  709.29     .06       0
Bank Sta=243.93,257.3
XS Rating Curve= 0 ,0
Exp/Cntr=0.3,0.1

Type RM Length L Ch R = 1 ,13721.7 ,94,93.9,93.9
XS GIS Cut Line= 3
     2357742.194      310459.075     2357885.424      310375.524
      2358295.58      310010.941
#Sta/Elev= 30
       0  726.16   17.54724.7827   39.42 723.326   91.45720.1757   99.71719.7278
  129.62717.8927   161.9  714.98   169.8  714.62   209.6  709.29   221.5   708.6
   245.4   708.5   249.3  708.09   253.8  706.68   257.3  706.09   268.8  706.62
   277.2  708.46     309     708  357.92709.4067  379.34711.3255   400.4   712.6
   412.4   712.2   420.3  713.36  430.61713.3823     468  713.26   559.5   715.5
  633.84 716.568  659.47717.2357  664.16 717.431  703.08718.1348   714.6  718.22
#Mann= 15 ,-1 , 0
       0     .08       0   17.54     .06       0   39.42     .08       0
   91.45     .06       0   99.71     .12       0  129.62    .016       0
   253.8    .045       0   268.8    .016       0  357.92     .08       0
  379.34    .016       0  430.61     .06       0  633.84     .08       0
  659.47     .12       0  664.16     .08       0  703.08     .06       0
Bank Sta=253.8,268.8
XS Rating Curve= 0 ,0
Exp/Cntr=0.3,0.1

Type RM Length L Ch R = 1 ,13627.8 ,204.1,205.5,202.9
XS GIS Cut Line= 2
     2357869.147      310524.179     2358324.877      310063.024
#Sta/Elev= 30
       0  725.39    43.8  722.46   60.63720.0379    71.6  718.37  108.83717.5627
   115.4  716.65   139.2   711.4   167.1  708.26     179  707.71   226.7  708.61
   230.7  708.26  237.57706.0686   242.6  705.26   250.6  706.04   258.5  707.68
   274.4  708.41   294.3  707.57   318.2  712.12  330.53713.2386     350  712.71
   365.9  713.01   369.9  713.27  376.78715.6184  389.82715.6091   409.7  715.32
   477.3  716.52     533  719.26   568.8  720.26   592.7  719.54   648.4  720.92
#Mann= 8 ,-1 , 0
       0     .06       0   60.63    .016       0  108.83     .12       0
  237.57    .045       0   250.6     .12       0  330.53    .016       0
  376.78     .12       0  389.82     .06       0
Bank Sta=237.57,250.6
XS Rating Curve= 0 ,0
Exp/Cntr=0.3,0.1

Type RM Length L Ch R = 1 ,13422.2 ,341.6,344.2,345.4
XS GIS Cut Line= 4
      2358070.97      310671.748     2358078.745      310599.196
      2358215.79       310432.48     2358446.404       310149.83
#Sta/Elev= 30
       0  720.19   52.67715.8835    65.3  715.61      73   714.8      85  714.88
   96.04714.0436   112.9  712.29   136.9  710.66   160.9  706.52   172.9  706.84
   188.9  708.58   216.8  706.45   236.8  707.26   256.8  705.55   264.8  704.41
  271.45 705.343   284.8  708.52   328.4  713.41  338.48 713.654   356.2  714.54
   364.1   714.3   368.1  714.68     372  715.98  379.46716.5833   391.9  716.01
   463.2  717.17   542.6  719.31   574.3  721.05   594.1  721.36   653.6   723.7
#Mann= 7 ,-1 , 0
       0     .06       0   52.67    .016       0   96.04     .12       0
   256.8    .045       0  271.45     .12       0  338.48    .016       0
  379.46     .06       0
Bank Sta=256.8,271.45
XS Rating Curve= 0 ,0
Exp/Cntr=0.3,0.1

Type RM Length L Ch R = 1 ,13078   ,298.8,297.2,295.7
XS GIS Cut Line= 2
     2358284.078      310857.295      2358705.33      310403.555
#Sta/Elev= 30
       0  725.58   31.54722.7148    47.9  720.01    63.9  719.55   75.55 717.081
    99.9  712.81   107.8  710.18   127.8  707.48   163.8  706.06   203.7  705.52
   215.7  705.87   239.7  704.05   247.7  704.72  254.33703.9226   263.6  702.82
   269.3703.8683   275.6  705.26   291.6  705.13   299.6  705.68   315.6   709.7
   327.5  711.84  358.44714.5438   379.5  716.02   391.5  715.97  403.12717.0025
   468.7  720.38  486.42 721.147  544.24724.7684  568.21725.4525   619.1  724.64
#Mann= 11 ,-1 , 0
       0     .06       0   31.54    .016       0   75.55     .12       0
  254.33    .045       0   269.3     .12       0  358.44    .016       0
  403.12     .06       0   468.7     .08       0  486.42     .06       0
  544.24     .08       0  568.21     .06       0
Bank Sta=254.33,269.3
XS Rating Curve= 0 ,0
Exp/Cntr=0.3,0.1

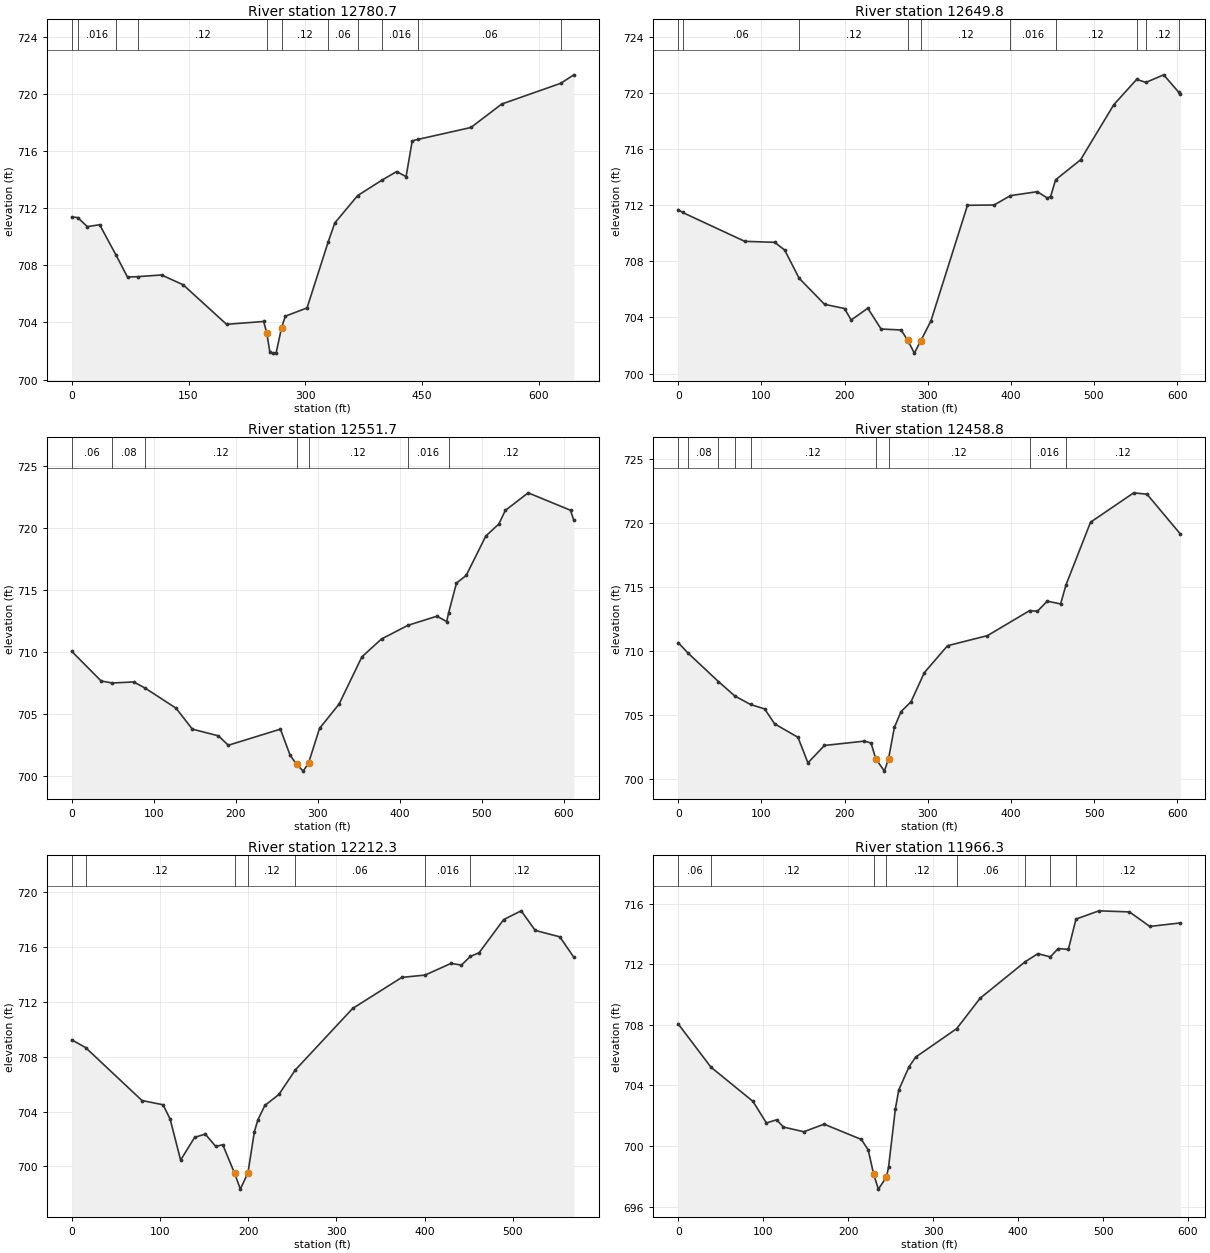
Type RM Length L Ch R = 1 ,12780.7 ,130.2,130.9,131.4
XS GIS Cut Line= 3
     2358518.887      311061.722     2358858.514       310646.14
     2358871.535      310538.719
#Sta/Elev= 30
       0   711.4    7.72711.3506    19.9  710.72    35.8  710.85   56.88708.7213
    71.6  707.18   85.61707.2144   115.3  707.33   143.1  706.64   198.8  703.87
   246.5  704.07   250.5  703.25   254.4  701.94   258.4  701.85   262.4  701.85
  269.44703.6247   274.3  704.44   302.2  705.02  329.37709.6481   337.9  710.98
  367.27712.8967  399.08714.0001   417.4  714.58   429.4  714.22   437.3  716.73
  444.64716.8328   512.8  717.67   552.2  719.31  628.18720.7695   644.9  721.36
#Mann= 11 ,-1 , 0
       0     .12       0    7.72    .016       0   56.88     .06       0
   85.61     .12       0   250.5    .045       0  269.44     .12       0
  329.37     .06       0  367.27     .12       0  399.08    .016       0
  444.64     .06       0  628.18     .12       0
Bank Sta=250.5,269.44
XS Rating Curve= 0 ,0
Exp/Cntr=0.3,0.1

Type RM Length L Ch R = 1 ,12649.8 ,98.9,98.1,97.3
XS GIS Cut Line= 2
      2358612.42      311140.064     2359007.385       310683.25
#Sta/Elev= 30
       0  711.69    5.27711.4873      80  709.43     116  709.36     128  708.81
  145.39706.8014     176  704.94     200  704.64     208  703.82     228  704.66
     244  703.18     268  703.11     276  702.38     284  701.46   291.9  702.36
   303.9  703.75   347.9     712   379.9  712.02  399.58712.6888   431.9  712.97
   443.9  712.52   447.9  712.62  453.86 713.814   483.9  715.24   523.9  719.17
  551.35720.9729  562.56720.7607   583.9   721.3  602.15720.0481   603.9  719.93
#Mann= 10 ,-1 , 0
       0    .016       0    5.27     .06       0  145.39     .12       0
     276    .045       0   291.9     .12       0  399.58    .016       0
  453.86     .12       0  551.35    .016       0  562.56     .12       0
  602.15     .06       0
Bank Sta=276,291.9
XS Rating Curve= 0 ,0
Exp/Cntr=0.3,0.1

Type RM Length L Ch R = 1 ,12551.7 ,96.4,92.9,89.8
XS GIS Cut Line= 2
      2358689.46      311198.875     2359089.851       310735.55
#Sta/Elev= 30
       0  710.07    35.8  707.68   49.29707.5159    75.6   707.6   89.77707.0936
   127.2  705.48   147.1  703.79   178.9  703.25   190.9  702.49   254.5  703.79
   266.4  701.67   274.4  700.94   282.3   700.4  288.87701.0683   302.2  703.85
   326.1  705.82   353.9  709.63   377.8  711.07  409.95712.1699   445.4  712.91
   457.3  712.48  459.73713.1968   469.2  715.58   481.1   716.2     505  719.38
   520.9  720.35   528.8  721.45   556.7  722.87   608.4  721.46   612.4  720.64
#Mann= 7 ,-1 , 0
       0     .06       0   49.29     .08       0   89.77     .12       0
   274.4    .045       0  288.87     .12       0  409.95    .016       0
  459.73     .12       0
Bank Sta=274.4,288.87
XS Rating Curve= 0 ,0
Exp/Cntr=0.3,0.1

Type RM Length L Ch R = 1 ,12458.8 ,226.8,246.5,243.4
XS GIS Cut Line= 2
     2358775.831      311258.988     2359119.799      310763.111
#Sta/Elev= 30
       0  710.65   11.99709.8209   48.34707.6015   68.12706.4679   86.97705.8072
   103.9  705.46   115.9  704.29   143.9  703.24   155.9  701.24   175.8   702.6
   223.8  702.94   231.8  702.79  237.31701.5726   247.8  700.59  252.75701.5505
   259.8  704.01   267.8  705.25   279.8  706.02   295.8   708.3   323.7  710.41
   371.7   711.2  422.56713.1652   431.6   713.1   443.6   713.9   459.6  713.68
  466.24715.2012   495.6  720.08   547.5  722.38   563.5  722.27   603.5  719.16
#Mann= 9 ,-1 , 0
       0     .06       0   11.99     .08       0   48.34     .12       0
   68.12     .06       0   86.97     .12       0  237.31    .045       0
  252.75     .12       0  422.56    .016       0  466.24     .12       0
Bank Sta=237.31,252.75
XS Rating Curve= 0 ,0
Exp/Cntr=0.3,0.1

Type RM Length L Ch R = 1 ,12212.3 ,242.4,246,243.8
XS GIS Cut Line= 2
     2358961.378      311338.849     2359212.029      310827.781
#Sta/Elev= 30
       0  709.24   15.67708.6763    79.6  704.81   103.5   704.5   111.5  703.46
   123.4  700.46   139.3  702.12   151.3  702.36   163.2  701.46   171.2  701.58
  184.68699.4846   191.1  698.34  199.75699.5372     207  702.53     211   703.4
   218.9  704.45   234.8  705.25   253.3707.0325   318.4  711.53   374.2   713.8
   400.5713.9684   429.9  714.82   441.8   714.7  451.81715.3298   461.8   715.6
   489.6  718.02   509.5  718.66   525.4  717.23   553.3  716.76   569.2  715.27
#Mann= 7 ,-1 , 0
       0     .06       0   15.67     .12       0  184.68    .045       0
  199.75     .12       0   253.3     .06       0   400.5    .016       0
  451.81     .12       0
Bank Sta=184.68,199.75
XS Rating Curve= 0 ,0
Exp/Cntr=0.3,0.1

Type RM Length L Ch R = 1 ,11966.3 ,310,320.3,314.9
XS GIS Cut Line= 2
     2359225.267      311442.798     2359252.828      310852.412
#Sta/Elev= 30
       0  708.06   38.48705.2059    87.9  702.95   103.8  701.52   115.8  701.73
   123.8  701.25   147.8  700.94   171.7  701.44   215.6  700.43   223.6  699.74
   230.1  698.12   235.6  697.15   245.1  697.95   247.6  698.62   255.6  702.45
   259.6   703.7   271.6  705.22   279.5  705.87   327.8707.7507   355.4  709.76
  408.38712.1667   423.3   712.7  437.95712.4885   447.3  713.04   459.2  712.98
  468.24 714.985   495.2  715.53   531.1  715.46   555.1   714.5     591  714.73
#Mann= 8 ,-1 , 0
       0     .06       0   38.48     .12       0   230.1    .045       0
   245.1     .12       0   327.8     .06       0  408.38     .12       0
  437.95    .016       0  468.24     .12       0
Bank Sta=230.1,245.1
XS Rating Curve= 0 ,0
Exp/Cntr=0.3,0.1