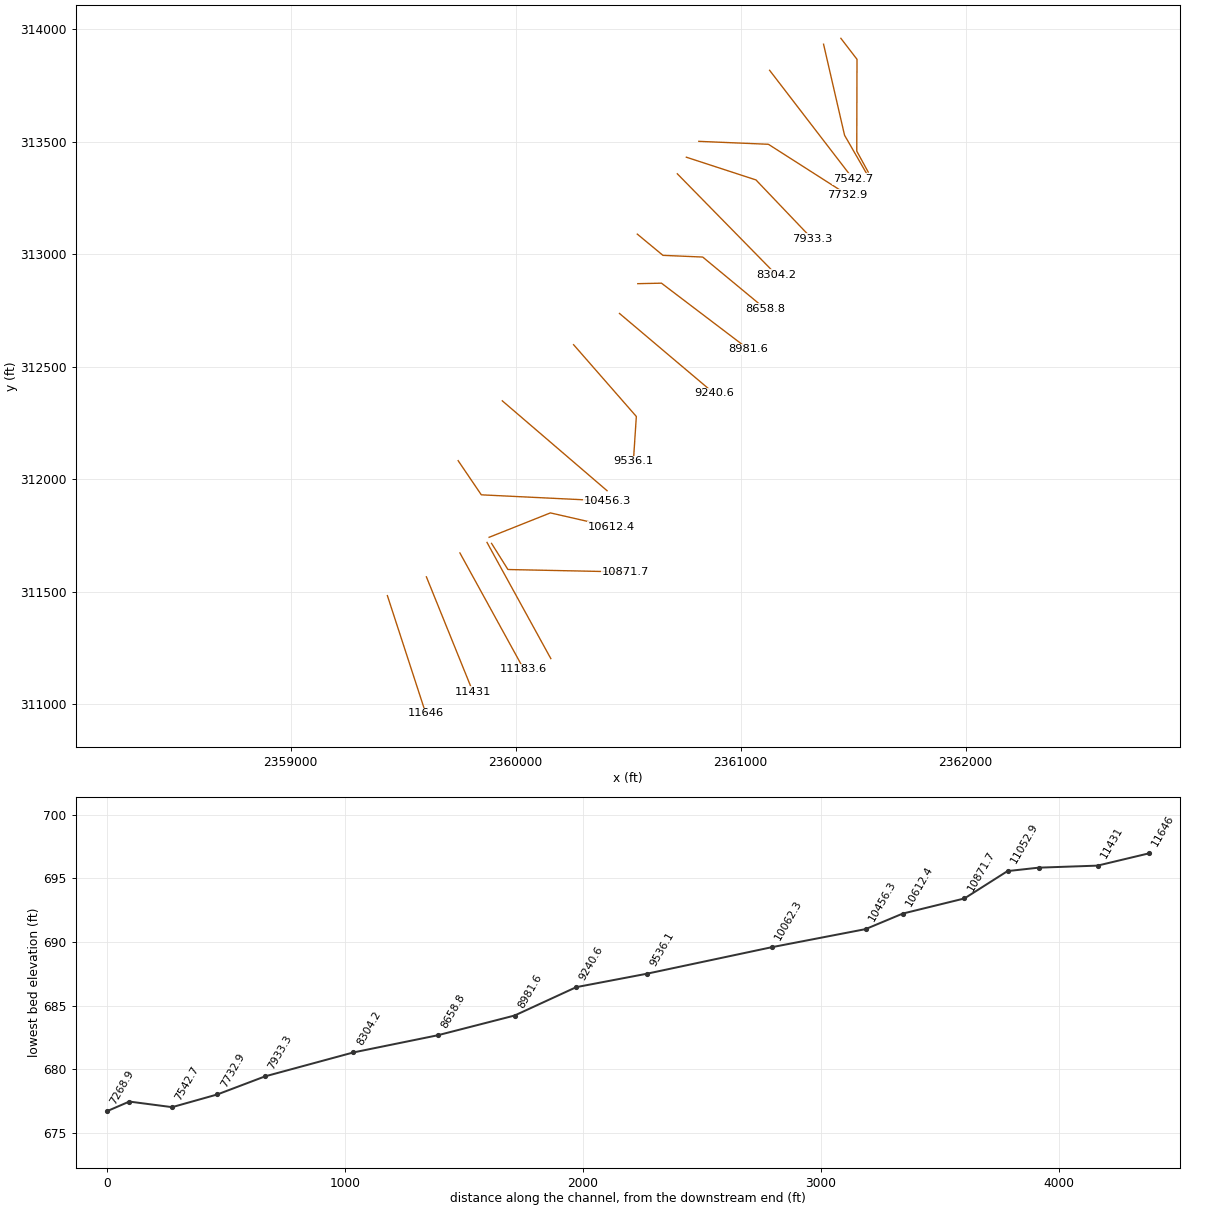
HEC-RAS study MILLCREEK1.prj: MILLCREEK1

--- MILLCREEK1.g01 (geometry) --- (continued)

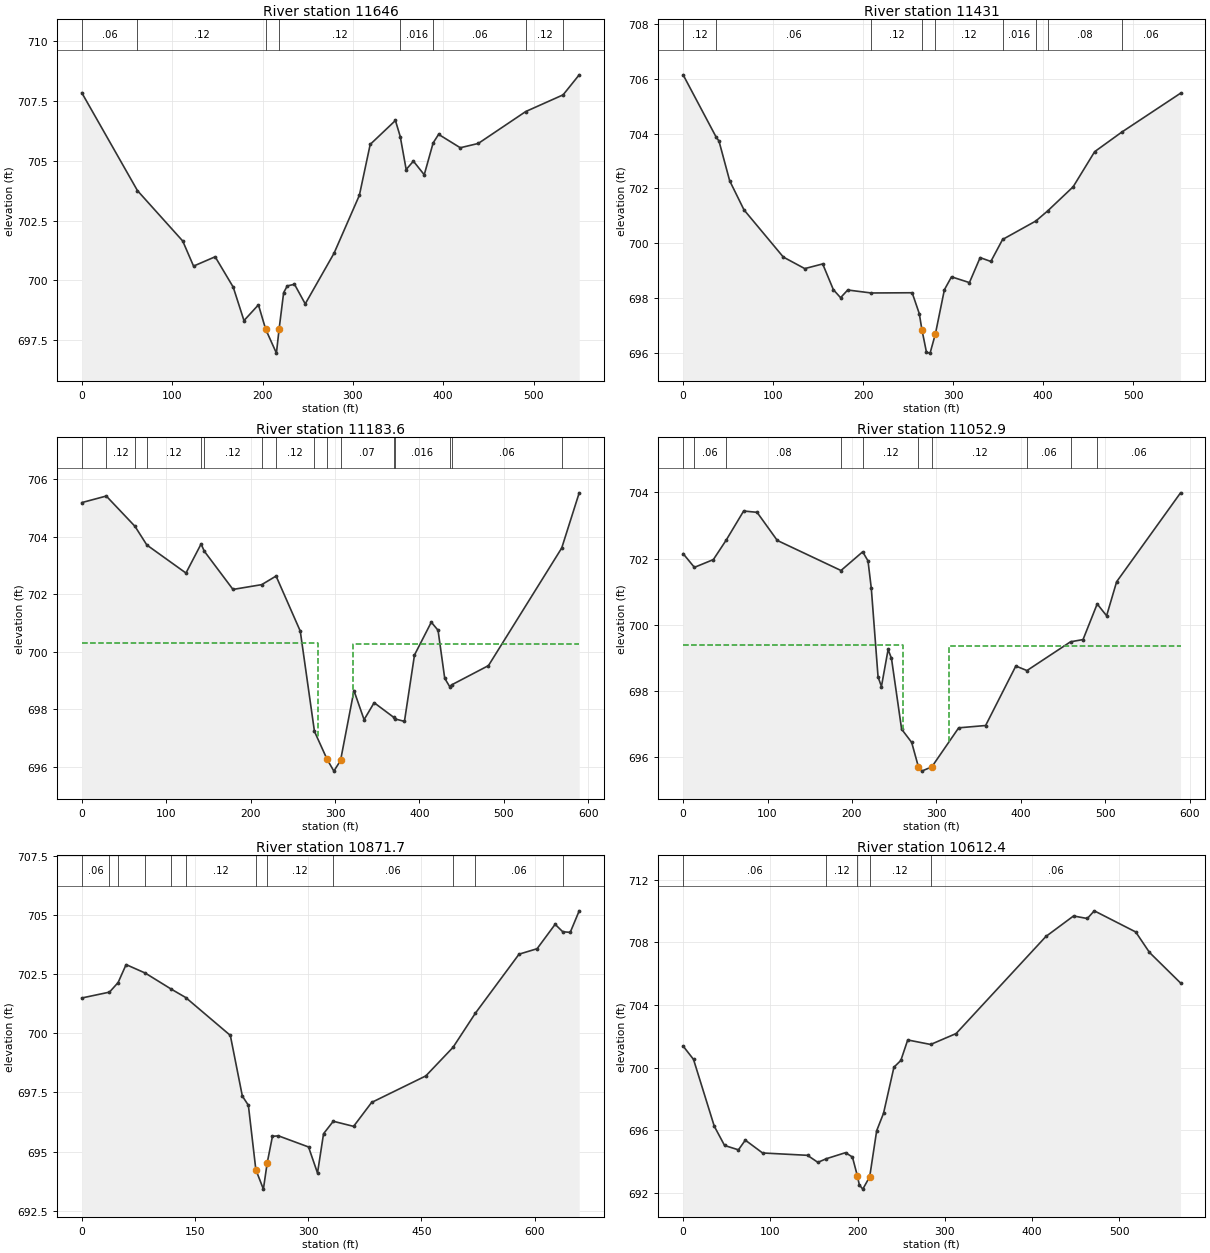
Type RM Length L Ch R = 1 ,11646   ,213.3,215,217.2
XS GIS Cut Line= 2
     2359429.694      311481.861     2359600.267      310958.423
#Sta/Elev= 30
       0  707.85   61.64 703.755   111.7  701.65   123.7   700.6   147.6  700.99
   167.6  699.72   179.5  698.32   195.5  698.98   203.5  697.96   215.4  696.96
  218.39697.9717   223.4  699.49   227.4  699.77   235.4  699.84   247.3  699.02
   279.2  701.14   307.2  703.56   319.2  705.69   347.1  706.69  352.45706.0177
     359  704.64     367  704.99     379  704.42  388.84705.7518   394.9  706.11
   418.9  705.55   438.8  705.73  491.34707.0652  532.66707.7621   550.5   708.6
#Mann= 8 ,-1 , 0
       0     .06       0   61.64     .12       0   203.5    .045       0
  218.39     .12       0  352.45    .016       0  388.84     .06       0
  491.34     .12       0  532.66     .06       0
Bank Sta=203.5,218.39
XS Rating Curve= 0 ,0
Exp/Cntr=0.3,0.1

Type RM Length L Ch R = 1 ,11431   ,244.6,247.4,246
XS GIS Cut Line= 2
     2359603.088      311565.303     2359810.337       311053.15
#Sta/Elev= 30
       0  706.14   36.75703.8672    39.8  703.73    51.7  702.28    67.6  701.22
   111.3   699.5   135.1  699.08     155  699.25   166.9  698.31   174.9  698.02
   182.8   698.3     209698.1915   254.4   698.2   262.3  697.44   265.2  696.86
   270.3  696.03   274.3     696   280.2   696.7   290.2  698.31   298.1  698.78
     318  698.57   329.9  699.48   341.8  699.34  354.83700.1409  391.76700.8139
  404.78701.1776   433.2  702.06   457.1  703.34  487.01 704.048   552.5  705.47
#Mann= 9 ,-1 , 0
       0     .12       0   36.75     .06       0     209     .12       0
   265.2    .045       0   280.2     .12       0  354.83    .016       0
  391.76     .06       0  404.78     .08       0  487.01     .06       0
Bank Sta=265.2,280.2
XS Rating Curve= 0 ,0
Exp/Cntr=0.3,0.1

Type RM Length L Ch R = 1 ,11183.6 ,131,130.8,131.2
XS GIS Cut Line= 2
     2359752.051      311671.584     2360035.723      311155.203
#Sta/Elev= 30
       0  705.18   29.01705.4084      63 704.355   77.07703.7049   123.4  702.73
   141.3  703.74  145.17703.4878   179.1  702.16   213.1702.3262  230.14702.6253
   258.8  700.71  275.59697.2222   290.6  696.25   298.6  695.84   306.5  696.21
   322.4  698.64   334.4  697.63   346.3  698.22  369.59697.7092  371.25697.6554
   382.2  697.57   394.1  699.88     414  701.02     422  700.74   429.9  699.07
  435.81698.7773  437.96698.8382   481.7  699.51  568.48703.5998   589.2  705.52
#Mann= 16 ,-1 , 0
       0     .06       0   29.01     .12       0      63     .08       0
   77.07     .12       0   141.3     .08       0  145.17     .12       0
   213.1     .08       0  230.14     .12       0  275.59     .07       0
   290.6    .045       0   306.5     .07       0  369.59     .12       0
  371.25    .016       0  435.81     .12       0  437.96     .06       0
  568.48     .08       0
#XS Ineff= 2 , 0
          279.88  700.28  320.74          700.26
Permanent Ineff=
       F       F
Bank Sta=290.6,306.5
XS Rating Curve= 0 ,0
Exp/Cntr=0.3,0.1

Type RM Length L Ch R = 1 ,11052.9 ,154.9,181.1,190.3
XS GIS Cut Line= 2
     2359872.494      311718.241     2360156.165      311201.861
#Sta/Elev= 30
       0  702.15   13.33 701.735    35.8  701.97   51.04702.5606    71.7  703.44
    87.6   703.4   111.5  702.55  186.99  701.64  212.71702.2057     219  701.93
   222.9   701.1   230.9  698.42   234.9  698.13   242.8  699.25   246.8  698.98
   258.8  696.84   270.7  696.44   278.7   695.7   282.6  695.57   294.6   695.7
   326.4  696.88   358.3  696.95   394.1  698.75  407.28698.6128  458.91699.4833
   473.7  699.55  490.49700.6289   501.6  700.27   513.5   701.3   589.2  703.99
#Mann= 10 ,-1 , 0
       0     .12       0   13.33     .06       0   51.04     .08       0
  186.99     .06       0  212.71     .12       0   278.7    .045       0
   294.6     .12       0  407.28     .06       0  458.91     .08       0
  490.49     .06       0
#XS Ineff= 2 , 0
          260.06  699.39  315.17          699.35
Permanent Ineff=
       F       F
Bank Sta=278.7,294.6
XS Rating Curve= 0 ,0
Exp/Cntr=0.3,0.1

Type RM Length L Ch R = 1 ,10871.7 ,249.8,259.3,268.4
XS GIS Cut Line= 3
     2359892.802      311713.957     2359965.502      311597.855
      2360487.42      311587.004
#Sta/Elev= 30
       0  701.49    36.7701.7377   48.14702.1426    58.7   702.9   84.02702.5433
  118.53 701.864  137.66701.5103   196.8  699.91   212.7  697.35   220.7  696.96
   230.6  694.24   240.6  693.42   245.6  694.52   252.6  695.65   260.5  695.67
   300.4   695.2   312.3   694.1   320.3  695.76  333.18696.2851   360.1  696.07
     384  697.08   455.8   698.2  491.84699.4062  521.36700.8444   579.3  703.34
   603.2  703.57   627.1   704.6  637.16704.2885   647.1  704.26     659  705.17
#Mann= 12 ,-1 , 0
       0     .06       0    36.7     .12       0   48.14     .08       0
   84.02     .06       0  118.53     .08       0  137.66     .12       0
   230.6    .045       0   245.6     .12       0  333.18     .06       0
  491.84     .08       0  521.36     .06       0  637.16     .12       0
Bank Sta=230.6,245.6
XS Rating Curve= 0 ,0
Exp/Cntr=0.3,0.1

Type RM Length L Ch R = 1 ,10612.4 ,165.5,156.1,146.4
XS GIS Cut Line= 3
     2359881.951      311741.084     2360154.304      311849.591
     2360424.486      311787.742
#Sta/Elev= 30
       0  701.37    11.9  700.52    35.7  696.25    47.5  695.02    63.4  694.74
    71.3  695.36    91.1  694.54   142.6  694.39   154.5  693.94  164.13694.1719
   186.2  694.56   194.1  694.28  199.83693.0676     202   692.5     206  692.23
   213.9  693.02   221.9  695.96   229.8  697.08   241.7  700.02   249.6  700.45
   257.5  701.76  283.81701.4722     313  702.17   415.9  708.37   447.6  709.68
   463.4  709.52   471.4  710.01   518.9  708.66   534.7  707.35   570.3   705.4
#Mann= 5 ,-1 , 0
       0     .06       0  164.13     .12       0  199.83    .045       0
   213.9     .12       0  283.81     .06       0
Bank Sta=199.83,213.9
XS Rating Curve= 0 ,0
Exp/Cntr=0.3,0.1

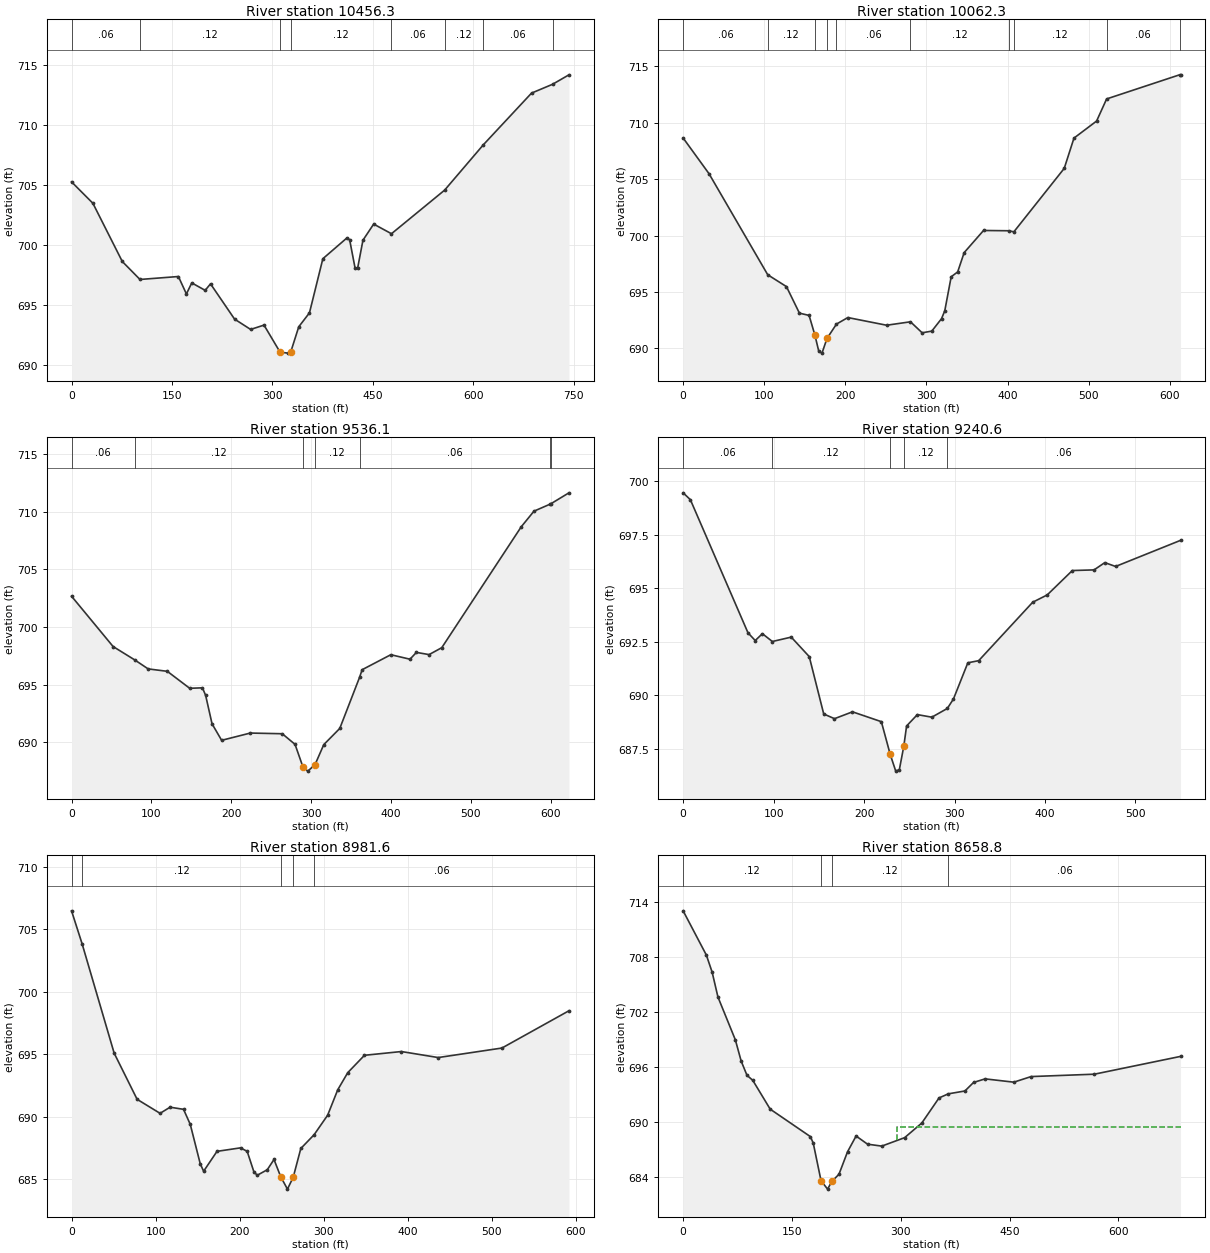
Type RM Length L Ch R = 1 ,10456.3 ,398.9,393.9,376.4
XS GIS Cut Line= 3
     2359744.147      312081.796     2359847.229      311929.886
      2360406.04      311902.759
#Sta/Elev= 30
       0  705.25    31.9  703.47    75.8  698.63  102.23697.1346   159.6  697.38
   171.6  695.93   179.6  696.85   199.6  696.23   207.6  696.77   243.5  693.84
   267.5  692.98   287.5  693.34   311.5  691.09   323.4  691.01   327.4   691.1
   339.4   693.2   355.4  694.36   375.4  698.86   411.4  700.59   415.4  700.44
   423.4  698.12   427.4  698.09   435.3   700.4   451.3  701.74  477.89700.9376
  557.31704.5635  615.34708.3467   687.1  712.63  718.46 713.362     743  714.15
#Mann= 8 ,-1 , 0
       0     .06       0  102.23     .12       0   311.5    .045       0
   327.4     .12       0  477.89     .06       0  557.31     .12       0
  615.34     .06       0  718.46     .08       0
Bank Sta=311.5,327.4
XS Rating Curve= 0 ,0
Exp/Cntr=0.3,0.1

Type RM Length L Ch R = 1 ,10062.3 ,517.6,526.3,519.5
XS GIS Cut Line= 2
     2359940.545      312347.638      2360406.04      311948.332
#Sta/Elev= 30
       0  708.64    31.9  705.48  104.32696.5285   127.4  695.48   143.4  693.13
   155.3  692.93  162.46  691.19   167.3  689.74   171.2  689.59   177.4 690.892
  189.07692.1621   203.1  692.74   250.9  692.06  280.32692.3648   294.7  691.39
   306.6  691.54   318.6  692.64   322.6  693.34   330.5  696.35   338.5  696.78
   346.5  698.49   370.4  700.45  401.73700.4247  407.77700.3286   469.9  705.95
   481.9  708.63   509.8  710.14  522.15712.0977  612.03714.2327   613.3  714.22
#Mann= 10 ,-1 , 0
       0     .06       0  104.32     .12       0  162.46    .045       0
   177.4     .12       0  189.07     .06       0  280.32     .12       0
  401.73     .06       0  407.77     .12       0  522.15     .06       0
  612.03     .08       0
Bank Sta=162.46,177.4
XS Rating Curve= 0 ,0
Exp/Cntr=0.3,0.1

Type RM Length L Ch R = 1 ,9536.1  ,292.8,295.4,298.1
XS GIS Cut Line= 3
     2360257.385      312597.204     2360536.248      312278.193
     2360523.227      312079.626
#Sta/Elev= 30
       0  702.66      52   698.3   79.37697.1279    95.9  696.36   119.9  696.15
   147.9  694.68   163.9  694.72   167.9  694.06   175.9   691.6   187.9  690.17
   223.8   690.8   263.8  690.74   279.8  689.82   289.8  687.84   295.8   687.5
   304.8  688.06   315.8   689.8   335.8   691.2  360.61 695.636   363.8  696.29
   399.7  697.59   423.7   697.2   431.7  697.79   447.6   697.6   463.5   698.2
     563  708.68   578.9  710.03  598.73710.6274  600.41710.6863   622.7  711.62
#Mann= 7 ,-1 , 0
       0     .06       0   79.37     .12       0   289.8    .045       0
   304.8     .12       0  360.61     .06       0  598.73     .12       0
  600.41     .06       0
Bank Sta=289.8,304.8
XS Rating Curve= 0 ,0
Exp/Cntr=0.3,0.1

Type RM Length L Ch R = 1 ,9240.6  ,257,259,260.2
XS GIS Cut Line= 2
     2360461.378      312736.093       2360881.3      312381.275
#Sta/Elev= 30
       0  699.45       8  699.13    71.7  692.91    79.7  692.55    87.6  692.87
   98.61692.5049   119.5  692.71   139.4   691.8   155.4  689.12   167.3   688.9
   187.2  689.22   219.1  688.76   228.9  687.23     235  686.45     239  686.52
   243.9  687.61     247  688.56   258.9  689.09   274.9  688.97  291.99689.3765
   298.8  689.82   314.7  691.51   326.7  691.61   386.4  694.34   402.4  694.68
   430.2  695.82   454.2  695.85   466.1  696.19     478  696.01   549.8  697.23
#Mann= 5 ,-1 , 0
       0     .06       0   98.61     .12       0   228.9    .045       0
   243.9     .12       0  291.99     .06       0
Bank Sta=228.9,243.9
XS Rating Curve= 0 ,0
Exp/Cntr=0.3,0.1

Type RM Length L Ch R = 1 ,8981.6  ,309.3,322.8,330.4
XS GIS Cut Line= 3
     2360542.759      312868.471      2360648.01      312870.641
      2361035.38      312576.588
#Sta/Elev= 30
       0  706.47   12.54703.8405    50.7  695.09      78   691.4   105.3  690.28
   117.2  690.77   133.2   690.6   141.2   689.4   153.1  686.24   157.1  685.65
     173  687.24     201  687.52   208.9  687.24   216.9   685.6   220.9  685.33
   232.8  685.77   240.8  686.59   248.8  685.21   256.8  684.22  263.67685.1754
   272.7  687.47  288.48688.5671   304.6  690.13   316.6  692.16   328.5  693.53
   348.4  694.92   392.3  695.22   436.1  694.74   511.9   695.5   591.6  698.48
#Mann= 5 ,-1 , 0
       0     .06       0   12.54     .12       0   248.8    .045       0
  263.67     .12       0  288.48     .06       0
Bank Sta=248.8,263.67
XS Rating Curve= 0 ,0
Exp/Cntr=0.3,0.1

Type RM Length L Ch R = 1 ,8658.8  ,371.9,354.6,336.7
XS GIS Cut Line= 4
     2360540.588       313088.74     2360654.521      312994.339
     2360831.387      312986.744     2361109.165      312756.709
#Sta/Elev= 30
       0  713.01      32  708.19      40  706.32      48  703.61      72  698.94
      80  696.63      88  695.08      96  694.53     120  691.39   175.5  688.39
   179.4  687.67  190.07 683.592   199.1  682.67  204.98683.5098   214.8  684.29
   226.6  686.74   238.4  688.46   254.2  687.57   273.8  687.36   305.3  688.28
     329  689.88   352.7  692.61  365.44693.0579   388.4  693.37   400.3   694.3
   416.2  694.69   455.8  694.33   479.6  694.94   566.8   695.2   685.6  697.14
#Mann= 4 ,-1 , 0
       0     .12       0  190.07    .045       0  204.98     .12       0
  365.44     .06       0
#XS Ineff= 2 , 0
                          294.74           689.4
Permanent Ineff=
       F       F
Bank Sta=190.07,204.98
XS Rating Curve= 0 ,0
Exp/Cntr=0.3,0.1

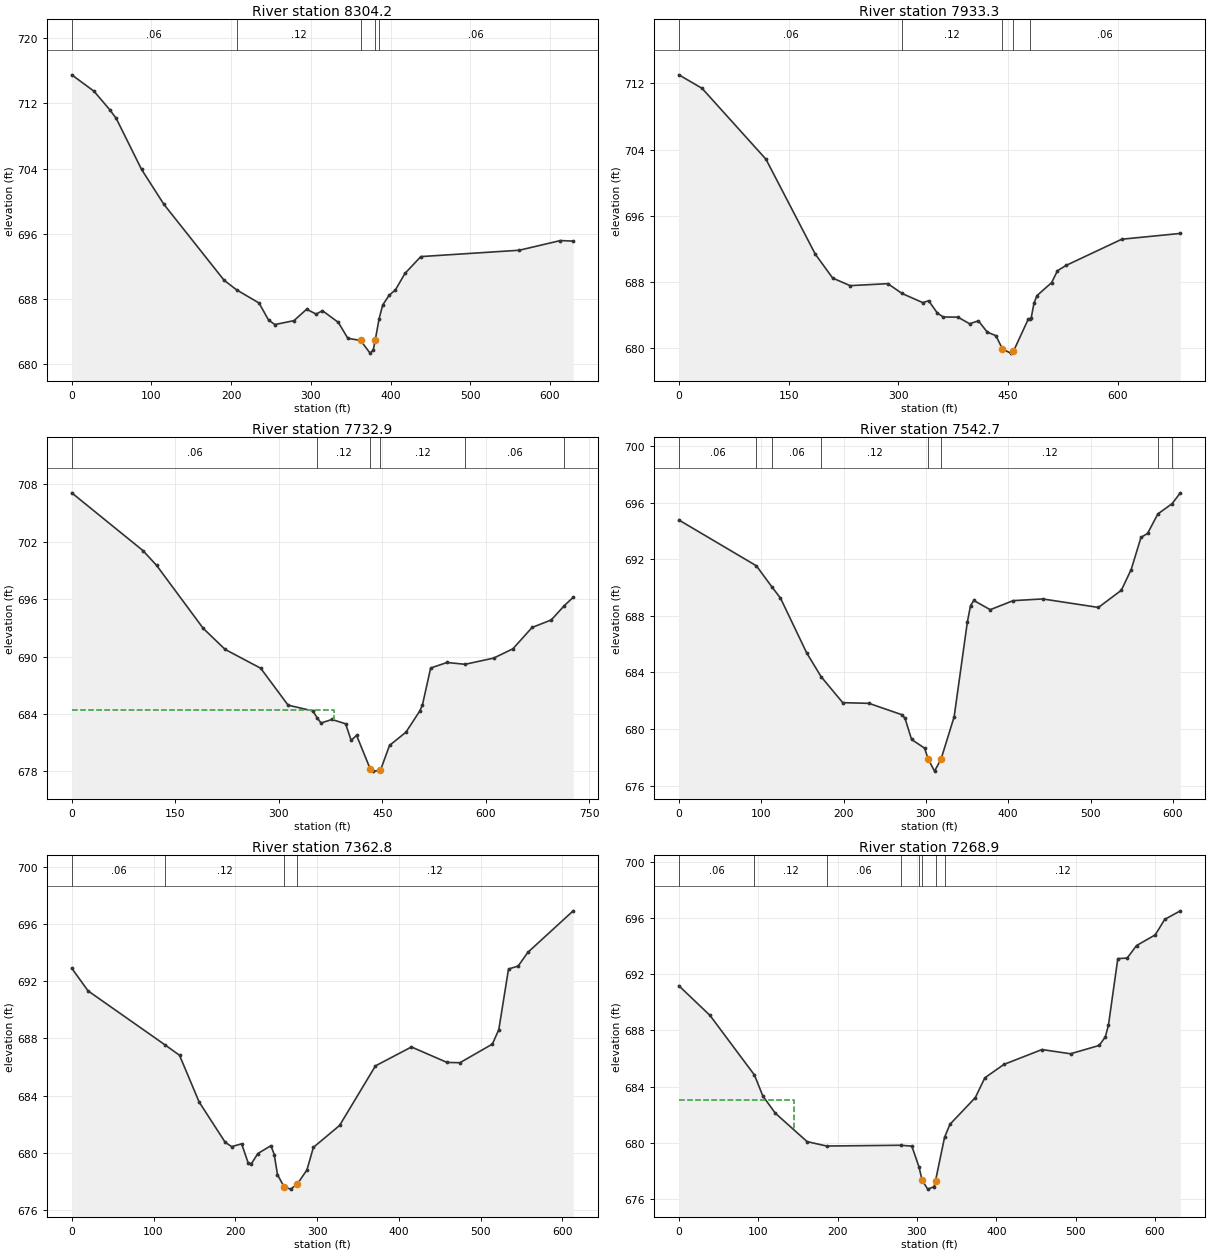
Type RM Length L Ch R = 1 ,8304.2  ,362.5,370.9,388.4
XS GIS Cut Line= 2
      2360718.54      313356.752     2361159.078      312907.534
#Sta/Elev= 30
       0  715.51    27.9   713.5    47.8  711.21    55.8  710.16    87.6  703.89
   115.5  699.62   191.1  690.28  206.97689.0856     235  687.48   246.9  685.39
   254.9  684.83   278.8  685.31   294.7  686.71   306.6  686.12   314.6  686.53
   334.5   685.1   346.4  683.14   362.4  682.88   374.3  681.32   378.3   681.7
  380.89682.9756   385.7685.5577   390.2  687.24   398.2  688.42   406.2   689.1
   418.1  691.11     438  693.18   561.5  693.96   613.2  695.15   629.2  695.08
#Mann= 5 ,-1 , 0
       0     .06       0  206.97     .12       0   362.4    .045       0
  380.89     .12       0   385.7     .06       0
Bank Sta=362.4,380.89
XS Rating Curve= 0 ,0
Exp/Cntr=0.3,0.1

Type RM Length L Ch R = 1 ,7933.3  ,194.4,200.4,206.2
XS GIS Cut Line= 3
     2360758.687      313430.537     2361067.932      313329.626
     2361316.413      313069.209
#Sta/Elev= 30
       0  713.01    31.7  711.38     119  702.83   186.4  691.38   210.2  688.49
     234  687.58   285.6  687.82  304.81686.6404   333.3  685.53   341.3  685.76
   353.3  684.26   361.3   683.8   381.3  683.78   397.3  682.98   409.3  683.34
   421.3  681.98   433.3  681.54   442.1  679.94   453.3  679.44   457.1  679.65
   477.3  683.52  479.93683.5989   481.3  683.64   485.3  685.49   489.3  686.38
   509.3  687.94   517.3  689.38   529.3  690.03   605.2  693.18   685.2  693.88
#Mann= 5 ,-1 , 0
       0     .06       0  304.81     .12       0   442.1    .045       0
   457.1     .12       0  479.93     .06       0
Bank Sta=442.1,457.1
XS Rating Curve= 0 ,0
Exp/Cntr=0.3,0.1

Type RM Length L Ch R = 1 ,7732.9  ,194.2,190.2,183.3
XS GIS Cut Line= 3
     2360814.026      313501.067     2361123.271      313488.046
     2361474.833      313263.436
#Sta/Elev= 30
       0  707.12   103.2  701.08     123  699.53   190.5  692.95   222.2  690.75
   273.8  688.78   313.5  684.92   349.2  684.32  355.65683.6015   361.2  683.05
   377.1  683.42   396.9  682.97   404.9  681.24   412.8  681.76   432.3  678.29
   436.7  678.02   447.3  678.09   460.5  680.71   484.3  682.09   504.2  684.29
   508.2  684.93   520.1   688.8   543.9  689.38  570.02 689.191   611.5  689.84
   639.3  690.81   667.1  693.04   694.9  693.83  713.97 695.337   726.7   696.2
#Mann= 6 ,-1 , 0
       0     .06       0  355.65     .12       0   432.3    .045       0
   447.3     .12       0  570.02     .06       0  713.97     .12       0
#XS Ineff= 2 , 0
           380.6   684.4
Permanent Ineff=
       F       F
Bank Sta=432.3,447.3
XS Rating Curve= 0 ,0
Exp/Cntr=0.3,0.1

Type RM Length L Ch R = 1 ,7542.7  ,188.9,179.9,184.2
XS GIS Cut Line= 2
     2361128.696      313816.822      2361499.79      313333.966
#Sta/Elev= 30
       0  694.77   94.13691.5327  113.06690.0361   123.4  689.25   155.2  685.38
   172.7683.6977     199  681.86   230.9  681.81   270.7  681.01   274.6  680.76
   282.6  679.26   298.5  678.64   302.5   677.9   310.5  677.02   318.4  677.87
   334.3  680.86   350.3  687.54   354.2  688.72   358.2  689.08   378.1  688.43
     406  689.07   441.8  689.19   509.5  688.59   537.3   689.8   549.3  691.27
   561.2  693.54   569.2  693.82  581.71695.1996  598.94695.9203     609  696.69
#Mann= 8 ,-1 , 0
       0     .06       0   94.13     .12       0  113.06     .06       0
   172.7     .12       0   302.5    .045       0   318.4     .12       0
  581.71     .06       0  598.94     .12       0
Bank Sta=302.5,318.4
XS Rating Curve= 0 ,0
Exp/Cntr=0.3,0.1

Type RM Length L Ch R = 1 ,7362.8  ,101.4,94,87.6
XS GIS Cut Line= 3
     2361368.496      313932.924     2361461.812      313528.193
     2361560.554      313356.752
#Sta/Elev= 30
       0  692.91      20  691.32  114.24687.5397   131.8  686.82   155.8  683.55
   187.7  680.73   195.7  680.43   207.7  680.63   215.7   679.3   219.7  679.24
   227.6  679.95   243.6   680.5   247.6  679.88   251.6  678.47   259.6677.6263
   267.6  677.46   275.6   677.8   287.6   678.8   295.5  680.38   327.5  681.91
   371.4  686.08   415.4   687.4   458.9  686.32   474.7   686.3   514.3   687.6
   522.2  688.61   534.1  692.85   545.9  693.06   557.8  694.02   613.2  696.92
#Mann= 4 ,-1 , 0
       0     .06       0  114.24     .12       0   259.6    .045       0
   275.6     .12       0
Bank Sta=259.6,275.6
XS Rating Curve= 0 ,0
Exp/Cntr=0.3,0.1

Type RM Length L Ch R = 1 ,7268.9  ,102.9,106.4,109.4
XS GIS Cut Line= 4
     2361445.536      313958.966     2361517.151       313865.65
     2361516.066      313457.664     2361567.064      313364.348
#Sta/Elev= 30
       0  691.17    39.2  689.06   95.19684.8235   105.9  683.32   121.6   682.1
   161.6  680.08  186.21 679.767  279.42679.8209   293.6  679.76  302.67678.2679
  306.48677.3438   313.6   676.7   321.6  676.87  323.47677.3001   334.8 680.376
   341.6  681.31   373.6  683.21   385.6  684.62   409.6  685.57   457.6  686.63
   493.6  686.33   529.6  686.92   537.4  687.52   541.4  688.37   553.2   693.1
     565  693.14   576.8  694.03   600.4  694.79   612.3  695.89     632   696.5
#Mann= 8 ,-1 , 0
       0     .06       0   95.19     .12       0  186.21     .06       0
  279.42     .12       0  302.67     .06       0  306.48    .045       0
  323.47     .06       0   334.8     .12       0
#XS Ineff= 2 , 0
          144.48  683.02
Permanent Ineff=
       F       F
Bank Sta=306.48,323.47
XS Rating Curve= 0 ,0
Exp/Cntr=0.3,0.1