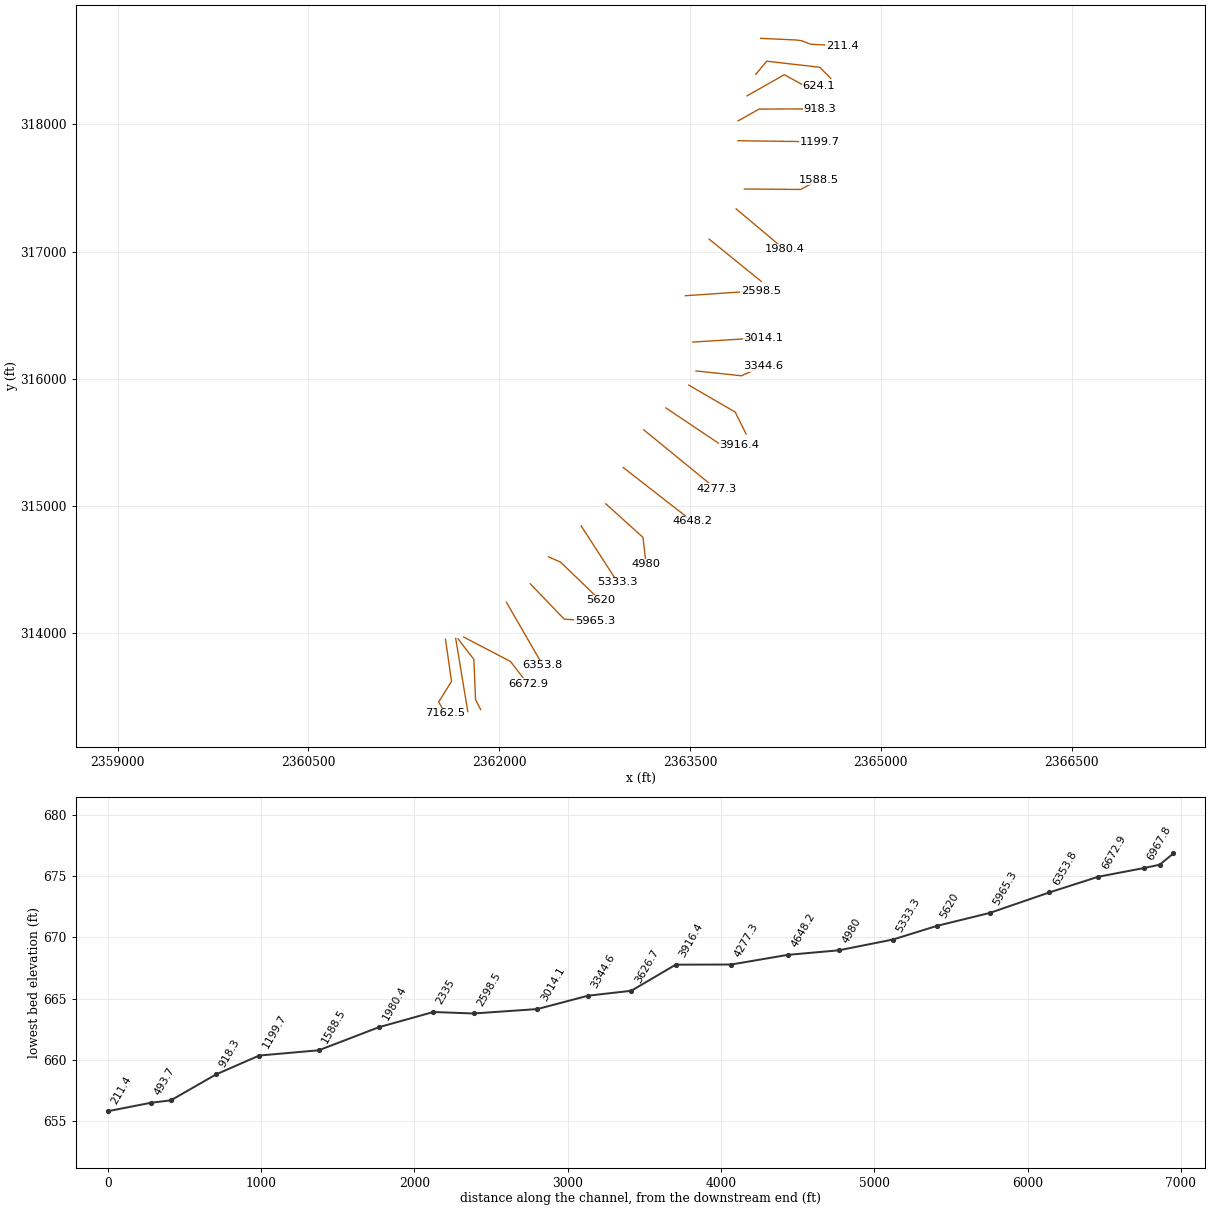
HEC-RAS study MILLCREEK1.prj: MILLCREEK1

--- MILLCREEK1.g01 (geometry) --- (continued)

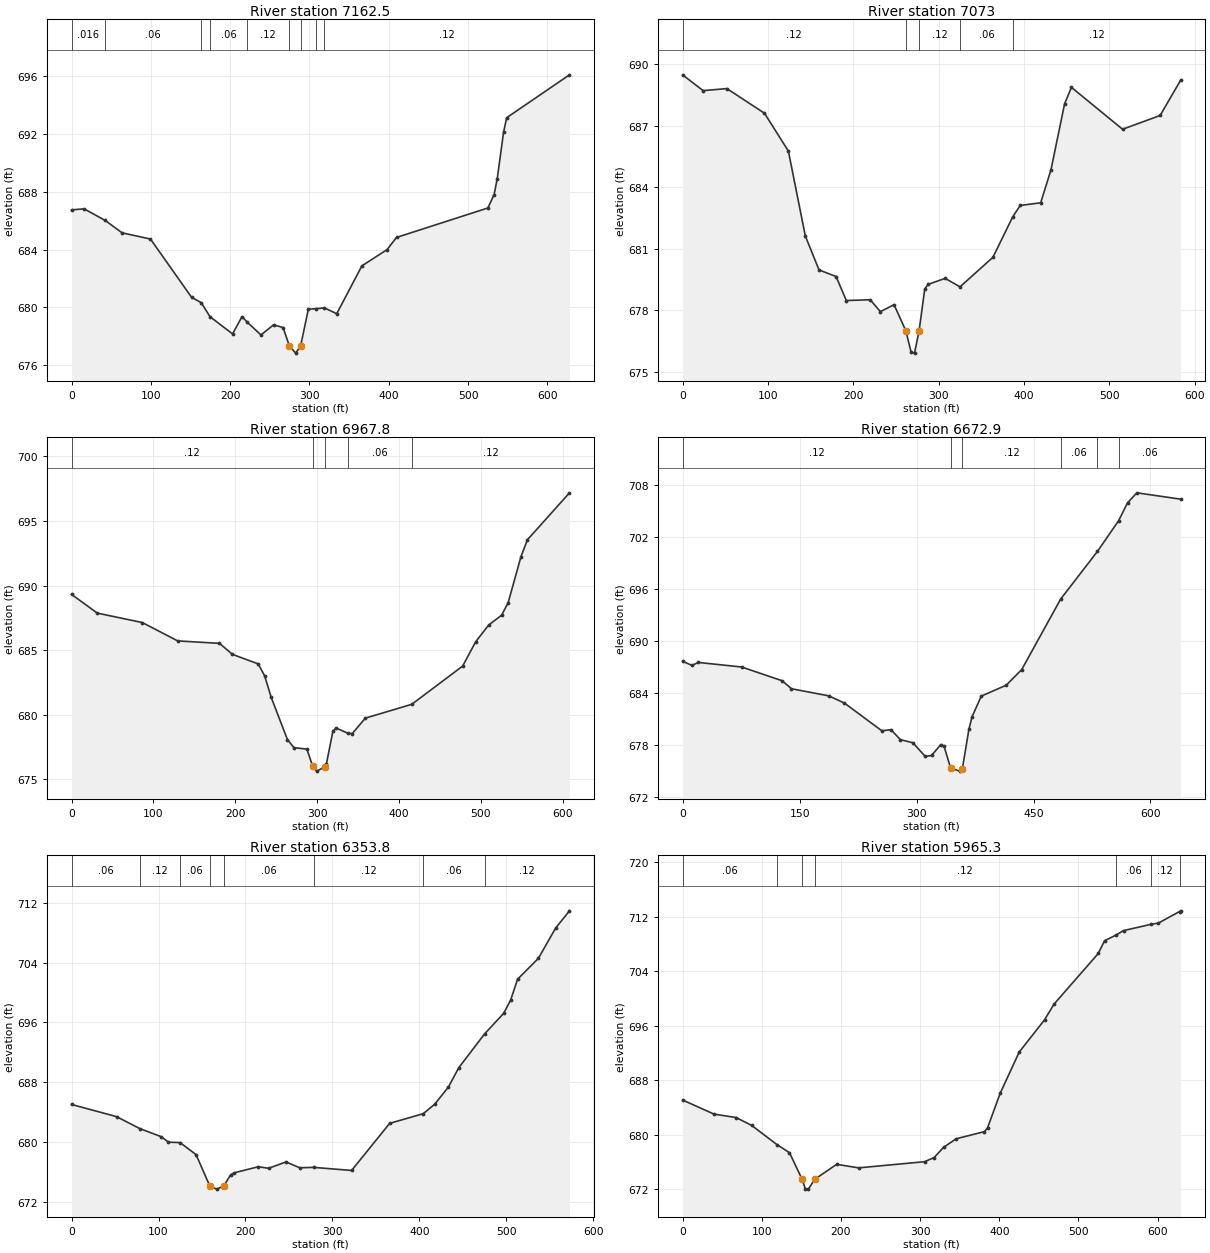
Type RM Length L Ch R = 1 ,7162.5  ,88,89.5,90.1
XS GIS Cut Line= 4
     2361577.915      313952.456     2361625.658      313621.509
     2361524.746      313459.834      2361574.66      313369.773
#Sta/Elev= 30
       0  686.76    15.9  686.83   42.33686.0294    63.7  685.17    99.5  684.74
   151.3  680.71  163.52680.3328  174.57679.3641     203  678.17     215  679.37
  221.35 678.994   238.8   678.1   254.8   678.8   266.7  678.61   274.7  677.34
   282.6  676.84  288.82 677.331   298.6  679.88  308.43679.9148  318.75 679.973
   334.4  679.57   366.1  682.88   397.9  684.01   409.8  684.85     525  686.89
   532.9  687.82   536.8  688.92   544.8  692.14   548.7  693.14   627.9  696.11
#Mann= 9 ,-1 , 0
       0    .016       0   42.33     .06       0  163.52     .12       0
  174.57     .06       0  221.35     .12       0   274.7    .045       0
  288.82     .12       0  308.43     .06       0  318.75     .12       0
Bank Sta=274.7,288.82
XS Rating Curve= 0 ,0
Exp/Cntr=0.3,0.1

Type RM Length L Ch R = 1 ,7073    ,108.7,105.2,101.7
XS GIS Cut Line= 2
     2361658.358      313959.173     2361753.548      313383.672
#Sta/Elev= 30
       0  689.47      24   688.7    51.9   688.8    95.9   687.6   123.9  685.76
   143.8  681.62   159.8  679.97   179.8  679.65   191.8  678.48   219.7  678.52
   231.7  677.94   247.7  678.28  261.49677.0092   267.7  675.97   271.7  675.92
  277.04677.0088   283.7  679.05   287.7  679.27   307.6  679.56  325.02679.1467
   363.6  680.59  386.64682.5484   395.5  683.11   419.5  683.24   431.5  684.84
   447.5  688.06   455.5  688.86   515.4  686.82   559.4  687.49   583.3   689.2
#Mann= 5 ,-1 , 0
       0     .12       0  261.49    .045       0  277.04     .12       0
  325.02     .06       0  386.64     .12       0
Bank Sta=261.49,277.04
XS Rating Curve= 0 ,0
Exp/Cntr=0.3,0.1

Type RM Length L Ch R = 1 ,6967.8  ,269.9,294.8,319.8
XS GIS Cut Line= 4
     2361676.656      313955.711     2361801.439      313794.035
      2361814.46      313477.195     2361854.608      313400.155
#Sta/Elev= 30
       0  689.32    31.4  687.87    86.4  687.14   129.6  685.72   180.7  685.53
   196.4  684.68     228  683.94   235.9  683.01   243.9  681.34   263.7  678.08
   271.6  677.46   287.5  677.34   294.6     676   299.4  675.64   309.6  675.97
   311.2  676.17   319.2  678.72   323.1  678.98  337.57678.5686     343  678.55
   358.8  679.74   415.6680.8127   477.7  683.77   493.6  685.65   509.4  686.94
   525.3  687.71   533.2  688.66     549  692.25   556.9  693.55   608.2  697.18
#Mann= 5 ,-1 , 0
       0     .12       0   294.6    .045       0   309.6     .12       0
  337.57     .06       0   415.6     .12       0
Bank Sta=294.6,309.6
XS Rating Curve= 0 ,0
Exp/Cntr=0.3,0.1

Type RM Length L Ch R = 1 ,6672.9  ,332,319.2,305.6
XS GIS Cut Line= 3
     2361721.144      313969.817     2362088.983      313777.759
     2362225.701      313600.893
#Sta/Elev= 30
       0  687.63      12  687.14      20  687.49    75.8  686.96   127.7  685.37
   139.6  684.45   187.5  683.63   207.5   682.8   255.4   679.6   267.3  679.72
   279.3  678.57   295.3  678.22   311.2  676.63   319.2  676.75   331.2  678.01
   335.2  677.84   343.7  675.29   355.1  674.94   358.7  675.18   367.1  679.75
   371.1   681.2     383   683.6     415  684.86   434.9  686.67   484.8 694.805
  531.89700.2968  559.03703.8353   570.6  705.92   582.6  707.07   638.5  706.34
#Mann= 6 ,-1 , 0
       0     .12       0   343.7    .045       0   358.7     .12       0
   484.8     .06       0  531.89     .12       0  559.03     .06       0
Bank Sta=343.7,358.7
XS Rating Curve= 0 ,0
Exp/Cntr=0.3,0.1

Type RM Length L Ch R = 1 ,6353.8  ,378.3,388.5,395.9
XS GIS Cut Line= 2
      2362056.43      314244.339     2362342.889      313748.463
#Sta/Elev= 30
       0     685    51.7  683.37    78.3681.7784   103.4  680.67   111.4  679.95
  124.83679.8903   143.2  678.28   159.1  674.05     167  673.66     175  674.08
   182.9  675.56   186.9  675.84   214.8  676.66   226.7  676.45   246.6   677.3
   262.5  676.52  278.58676.5714   322.1  676.16   365.9  682.47  404.49683.7617
   417.6  685.02   433.5  687.34   445.4  689.93  475.27694.4761   497.1  697.21
   505.1     699     513  701.77   536.9  704.56   556.8  708.63   572.7  710.93
#Mann= 8 ,-1 , 0
       0     .06       0    78.3     .12       0  124.83     .06       0
   159.1    .045       0     175     .06       0  278.58     .12       0
  404.49     .06       0  475.27     .12       0
Bank Sta=159.1,175
XS Rating Curve= 0 ,0
Exp/Cntr=0.3,0.1

Type RM Length L Ch R = 1 ,5965.3  ,341.8,345.3,347.2
XS GIS Cut Line= 3
     2362244.147      314388.654     2362511.075      314110.876
      2362754.13      314093.515
#Sta/Elev= 30
       0  685.07    39.7     683    67.5   682.5    87.4  681.33  119.29678.5159
     135  677.34   150.9  673.44   154.9  672.07   158.9  671.99   166.8  673.43
   194.6  675.63   222.4  675.11   305.8  676.02   317.7  676.63   329.6  678.12
   345.5  679.38   381.3  680.43   385.2     681   401.2  686.08   425.2  692.12
   457.1  696.83   469.1  699.14     525  706.58     533  708.45  547.24709.2744
     557  709.94  591.83710.8637     601  711.04  627.65712.7369   628.9  712.84
#Mann= 7 ,-1 , 0
       0     .06       0  119.29     .12       0   150.9    .045       0
   166.8     .12       0  547.24     .06       0  591.83     .12       0
  627.65     .06       0
Bank Sta=150.9,166.8
XS Rating Curve= 0 ,0
Exp/Cntr=0.3,0.1

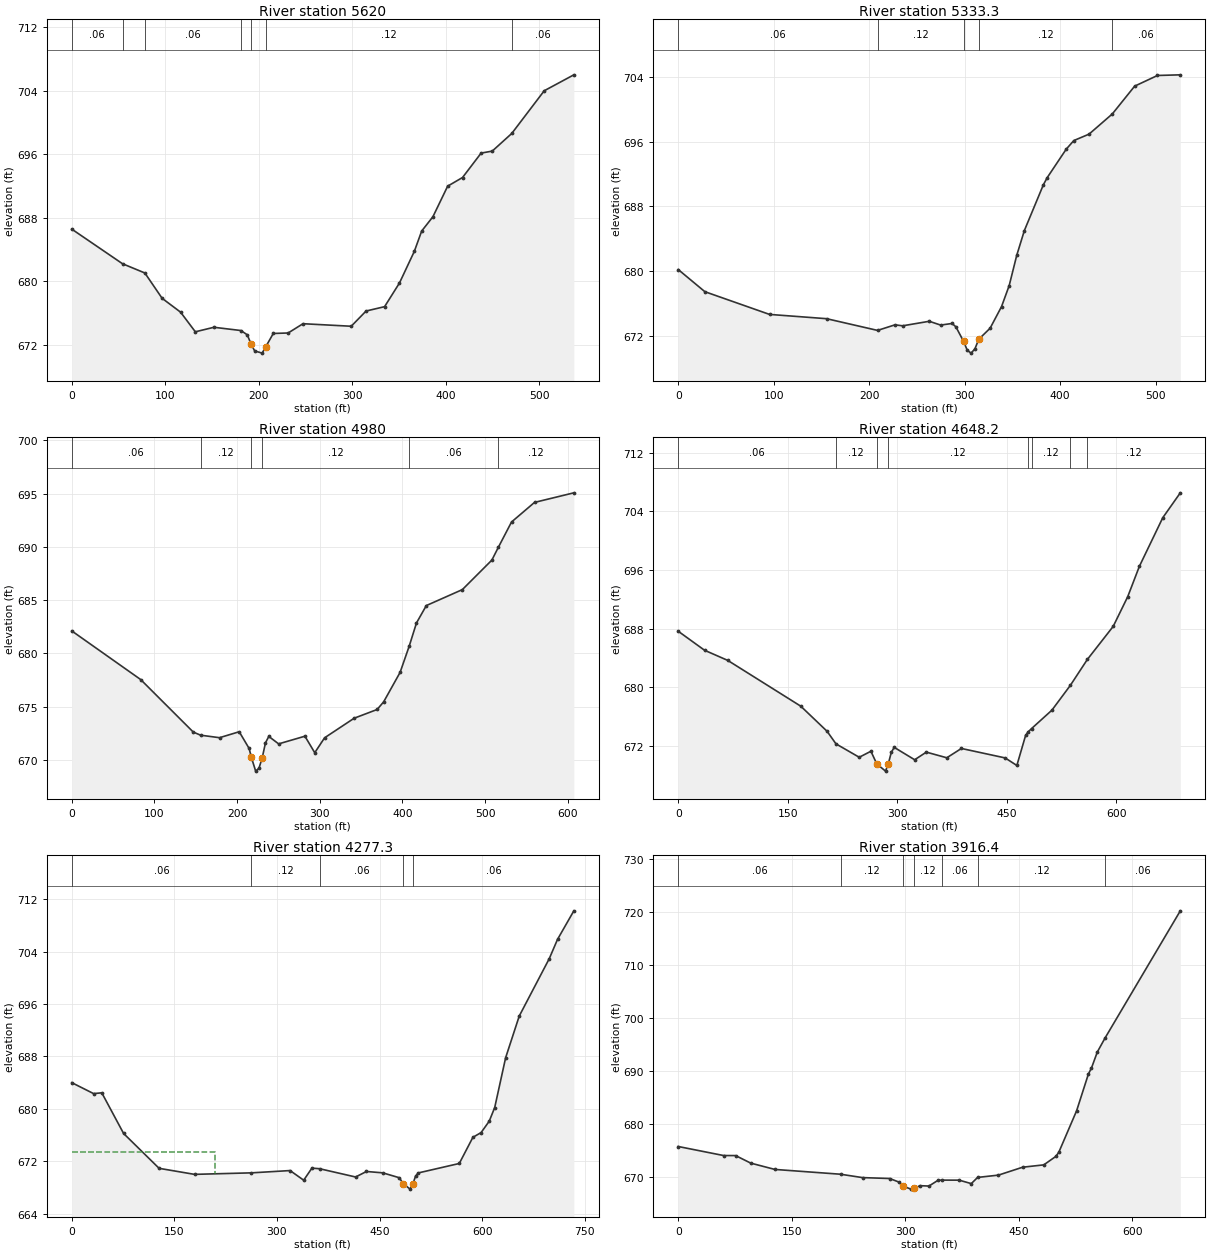
Type RM Length L Ch R = 1 ,5620    ,292.4,286.7,280.9
XS GIS Cut Line= 3
     2362388.462      314600.242     2362483.948      314557.924
     2362795.363       314257.36
#Sta/Elev= 30
       0  686.57   54.29682.2039   78.21681.0375    96.7  677.84   116.4   676.1
   132.2  673.62   152.1  674.19  180.92673.7811   187.8  673.24   191.8  672.08
   195.7  671.21   203.7  670.93   207.7  671.76   215.6  673.41   231.5  673.47
   247.4  674.64     299  674.32   314.9  676.24   334.7  676.79   350.6  679.77
   366.5  683.76   374.4  686.33   386.4  688.13   402.2  691.99   418.1  693.08
     438  696.16   449.9  696.41  470.75698.6323   505.5  704.02   537.2  706.03
#Mann= 7 ,-1 , 0
       0     .06       0   54.29     .12       0   78.21     .06       0
  180.92     .12       0   191.8    .045       0   207.7     .12       0
  470.75     .06       0
Bank Sta=191.8,207.7
XS Rating Curve= 0 ,0
Exp/Cntr=0.3,0.1

Type RM Length L Ch R = 1 ,5333.3  ,346,353.3,360.4
XS GIS Cut Line= 2
     2362645.623      314842.213     2362930.996      314400.589
#Sta/Elev= 30
       0  680.16    27.9  677.42    95.6  674.61   155.4  674.08  208.73672.6304
     227  673.32     235   673.2   262.9  673.76   274.8  673.29   286.8  673.49
   290.8  673.07   298.8  671.28   302.7  670.17   306.7  669.82   310.7  670.35
   314.7  671.53   326.6   672.9   338.6  675.58   346.6  678.18   354.5  681.92
   362.5  684.99   382.4  690.65   386.4  691.53   406.3  695.05   414.3  696.12
   430.2  696.91  454.56699.4063     478  702.85   501.9  704.17   525.8  704.25
#Mann= 5 ,-1 , 0
       0     .06       0  208.73     .12       0   298.8    .045       0
   314.7     .12       0  454.56     .06       0
Bank Sta=298.8,314.7
XS Rating Curve= 0 ,0
Exp/Cntr=0.3,0.1

Type RM Length L Ch R = 1 ,4980    ,330.1,331.8,333.1
XS GIS Cut Line= 3
     2362838.766      315016.909     2363130.649      314753.237
     2363155.606      314540.563
#Sta/Elev= 30
       0  682.11    83.4  677.54     147  672.61  155.84672.3163   178.8  672.08
   202.6  672.64   214.6  671.07  217.24670.2577   222.5  668.94   226.5  669.21
   230.4  670.18   234.4   671.6   238.4   672.2   250.3   671.5   282.1  672.22
     294  670.67   305.9  672.07   341.7  673.91   369.5  674.73   377.4  675.45
   397.3  678.22   408.4 680.706   417.1  682.86     429  684.49   472.6  685.99
   508.3  688.76  516.07689.9509   532.1  692.34   559.9  694.18   607.5  695.08
#Mann= 6 ,-1 , 0
       0     .06       0  155.84     .12       0  217.24    .045       0
   230.4     .12       0   408.4     .06       0  516.07     .12       0
Bank Sta=217.24,230.4
XS Rating Curve= 0 ,0
Exp/Cntr=0.3,0.1

Type RM Length L Ch R = 1 ,4648.2  ,371,370.9,370.5
XS GIS Cut Line= 2
     2362975.484      315302.282     2363518.019       314880.19
#Sta/Elev= 30
       0  687.64      36  685.05    67.9  683.66   167.8  677.42   203.8     674
  215.96672.2876   247.8  670.46   263.8  671.28   271.8  669.56   283.8  668.57
   287.7   669.6   291.7  671.13   295.7  671.81   323.7  670.12   339.7  671.16
   367.7  670.39   387.7  671.66   447.6  670.37   463.6  669.34   475.6  673.44
   479.1673.9213  483.69674.3669   511.6  676.88  536.85680.2621  560.16683.7989
   595.5   688.3   615.4  692.35   631.4   696.5   663.4  703.12   687.4  706.51
#Mann= 8 ,-1 , 0
       0     .06       0  215.96     .12       0   271.8    .045       0
   287.7     .12       0   479.1     .06       0  483.69     .12       0
  536.85     .06       0  560.16     .12       0
Bank Sta=271.8,287.7
XS Rating Curve= 0 ,0
Exp/Cntr=0.3,0.1

Type RM Length L Ch R = 1 ,4277.3  ,359.9,360.9,361.5
XS GIS Cut Line= 2
      2363137.16      315598.506     2363705.736      315134.096
#Sta/Elev= 30
       0  684.01    31.9  682.34    43.9  682.46    75.8  676.26   127.7  670.95
   179.5  670.03  262.75670.2614   319.2  670.61   339.1  669.14   351.1  670.98
  362.33670.8908     415  669.63   430.9  670.47   454.8  670.26   478.8  669.52
  484.56668.6244   494.7  667.78   498.7  668.54   502.7  669.78   506.7  670.25
   566.6  671.69   586.5  675.68   598.5   676.4   610.4  678.14   618.4  680.22
   634.4  687.82   654.3  694.17   698.2  702.92   710.2  705.84   734.1   710.2
#Mann= 5 ,-1 , 0
       0     .06       0  262.75     .12       0  362.33     .06       0
  484.56    .045       0   498.7     .06       0
#XS Ineff= 2 , 0
           209.7  673.38
Permanent Ineff=
       F       F
Bank Sta=484.56,498.7
XS Rating Curve= 0 ,0
Exp/Cntr=0.3,0.1

Type RM Length L Ch R = 1 ,3916.4  ,284.1,289.7,290.7
XS GIS Cut Line= 3
     2363310.771      315771.032     2363725.267      315493.254
     2363889.113      315479.148
#Sta/Elev= 30
       0   675.8    59.9   674.1    75.8  674.09    95.8  672.67   127.7  671.48
  214.41670.5778   243.5  669.94   279.4  669.77   291.4  669.11   297.1  668.35
   307.4  667.77   312.1  667.91   319.3  668.42   331.3  668.35   343.3  669.44
  348.62669.4666   371.2  669.46   387.2  668.81  395.57669.9748   423.1  670.41
   455.1   671.9     483  672.34     499  673.94   502.9  674.73   526.4  682.54
     542  689.47     546  690.58   553.8  693.62  564.09696.2727   663.4   720.2
#Mann= 7 ,-1 , 0
       0     .06       0  214.41     .12       0   297.1    .045       0
   312.1     .12       0  348.62     .06       0  395.57     .12       0
  564.09     .06       0
Bank Sta=297.1,312.1
XS Rating Curve= 0 ,0
Exp/Cntr=0.3,0.1

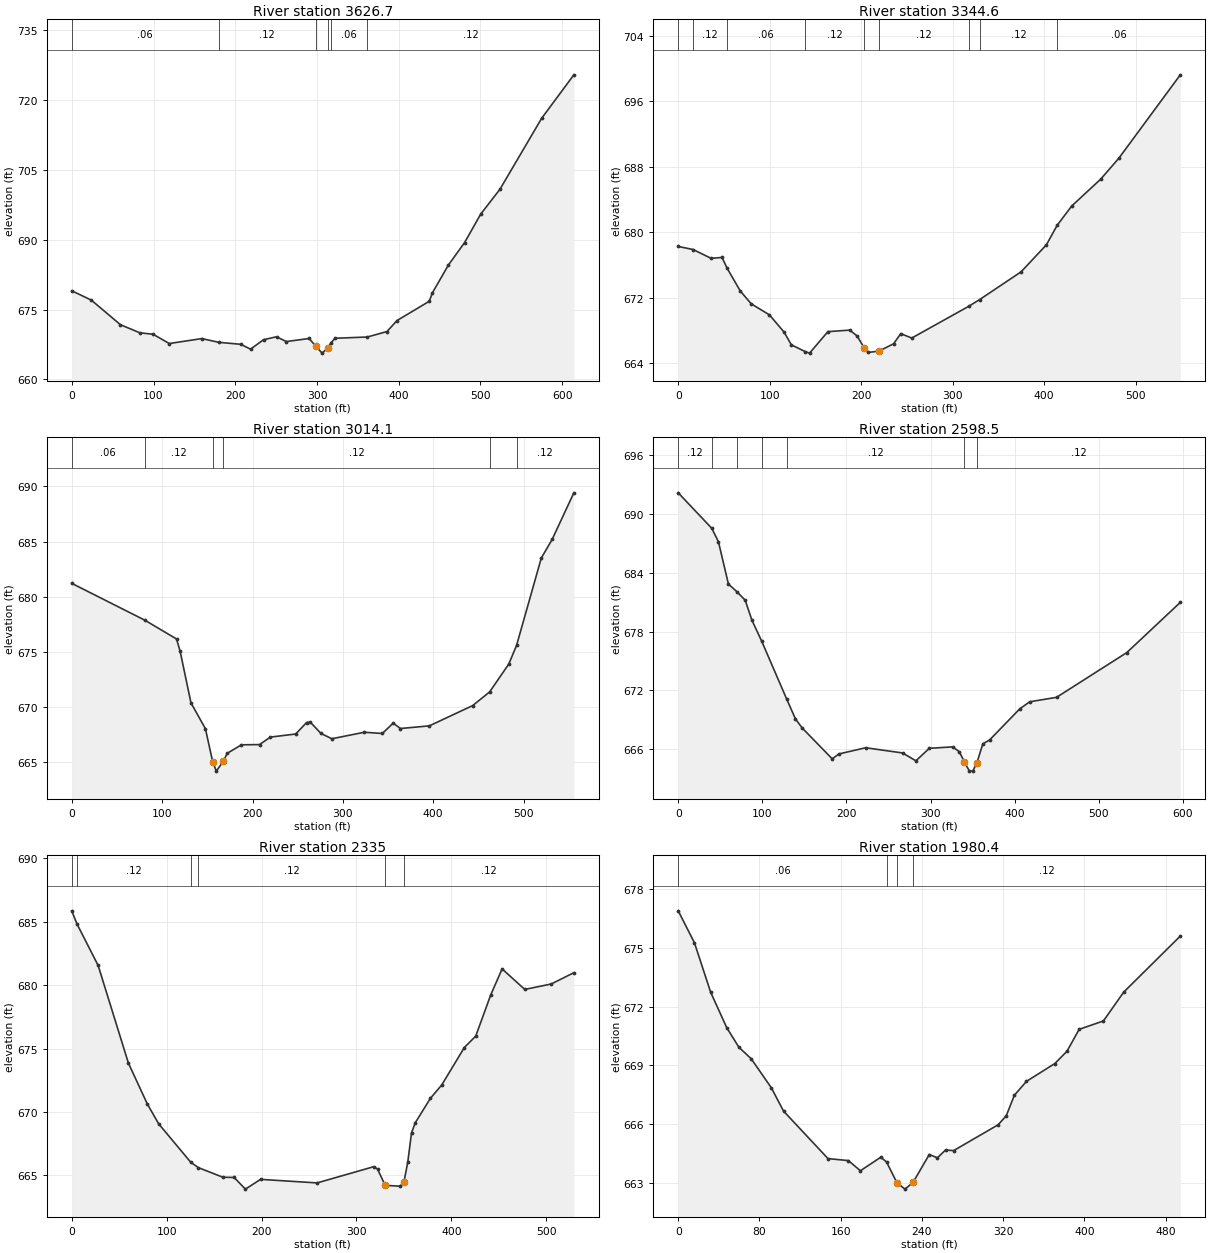
Type RM Length L Ch R = 1 ,3626.7  ,266.2,282.1,310
XS GIS Cut Line= 3
     2363490.892      315950.068     2363855.476       315738.48
     2363941.196      315565.954
#Sta/Elev= 30
       0  679.02    23.9  677.02    59.6  671.73    83.5  669.99    99.4   669.7
   119.3   667.7   159.1  668.76  179.64667.9666   206.8  667.53   218.7  666.49
   234.6  668.52   250.5  669.15   262.5  668.12   290.3  668.78   298.4  667.16
   306.2  665.64   313.4  666.76  317.36667.9104   322.1  668.83   361.6669.1002
   385.7  670.28   397.7  672.61   437.3  676.77   441.2  678.59   460.8  684.56
   480.5  689.35   500.2  695.46   523.8  700.81   574.9  716.06   614.2  725.37
#Mann= 6 ,-1 , 0
       0     .06       0  179.64     .12       0   298.4    .045       0
   313.4     .12       0  317.36     .06       0   361.6     .12       0
Bank Sta=298.4,313.4
XS Rating Curve= 0 ,0
Exp/Cntr=0.3,0.1

Type RM Length L Ch R = 1 ,3344.6  ,301.7,330.4,313.4
XS GIS Cut Line= 3
     2363547.316      316061.831     2363904.304      316023.853
     2364077.915      316100.893
#Sta/Elev= 30
       0  678.26    16.3677.8854    35.9  676.81    47.9  676.92   53.32675.6285
    67.8  672.83    79.8  671.26    99.7  669.91   115.7  667.81   123.7  666.25
  138.78665.4294   143.6  665.24   163.6  667.86   187.5  668.05   195.5  667.34
   203.4  665.87   207.4  665.32   219.4  665.48   235.4  666.38   243.3  667.62
   255.3  667.08   317.5  670.95  329.56671.7799   374.8  675.16   402.5  678.46
  414.24680.8388   430.2   683.2   461.9  686.48   481.7  689.03   548.9  699.21
#Mann= 9 ,-1 , 0
       0     .06       0    16.3     .12       0   53.32     .06       0
  138.78     .12       0   203.4    .045       0   219.4     .12       0
   317.5     .06       0  329.56     .12       0  414.24     .06       0
Bank Sta=203.4,219.4
XS Rating Curve= 0 ,0
Exp/Cntr=0.3,0.1

Type RM Length L Ch R = 1 ,3014.1  ,415.8,415.6,415
XS GIS Cut Line= 2
     2363522.359       316288.61      2364076.83      316323.332
#Sta/Elev= 30
       0   681.2   80.83677.8565   115.9  676.15   119.9  675.04   131.9  670.35
   147.9     668   155.9  665.01   159.9  664.15   167.9  665.06   171.9  665.76
   187.8  666.54   207.8  666.56   219.8  667.24   247.8  667.52   259.8  668.56
   263.8  668.61   275.8  667.57   287.8  667.09   323.7  667.68   343.7  667.57
   355.7  668.51   363.7  668.02   395.7  668.26   443.6   670.1  462.31671.3326
   483.6  673.87  492.22 675.569   519.6   683.5   531.6  685.19   555.6  689.42
#Mann= 6 ,-1 , 0
       0     .06       0   80.83     .12       0   155.9    .045       0
   167.9     .12       0  462.31     .06       0  492.22     .12       0
Bank Sta=155.9,167.9
XS Rating Curve= 0 ,0
Exp/Cntr=0.3,0.1

Type RM Length L Ch R = 1 ,2598.5  ,279.9,263.4,246.4
XS GIS Cut Line= 2
     2363463.766      316653.193     2364059.469      316693.341
#Sta/Elev= 30
       0  692.12   39.87688.5106    47.8  687.14    59.7  682.83   69.49682.0753
    79.6  681.19    87.6  679.16   99.11677.0411  129.13671.0897   139.3  669.12
   147.3  668.19   183.1  665.04   191.1  665.54   222.9  666.17   266.7  665.64
   282.6  664.84   298.5  666.11   326.4  666.26   334.4  665.75  340.19664.7193
   346.3  663.79   350.3   663.8   355.2664.6543   362.2  666.57   370.2  666.96
     406  670.12   417.9  670.85   449.8   671.3   533.4  675.86     597  680.97
#Mann= 7 ,-1 , 0
       0     .12       0   39.87     .08       0   69.49     .06       0
   99.11    .016       0  129.13     .12       0  340.19    .045       0
   355.2     .12       0
Bank Sta=340.19,355.2
XS Rating Curve= 0 ,0
Exp/Cntr=0.3,0.1

Type RM Length L Ch R = 1 ,2335    ,356.5,354.7,352.6
XS GIS Cut Line= 2
     2363650.397      317098.072     2364061.639      316764.956
#Sta/Elev= 30
       0  685.86    5.44684.8328    27.8  681.55    59.7  673.85    79.6  670.63
    91.5  669.07  125.31666.0378  133.33665.6086   159.2  664.85   171.1  664.83
     183  663.91     199  664.68   258.6   664.4   318.3  665.68   322.3  665.49
   330.3  664.21   346.2  664.14   350.2   664.5   354.2  666.06   358.1  668.35
   362.1  669.15     378  671.07     390  672.13   413.8  675.08   425.8  675.98
   441.7  679.25   453.6  681.28   477.5  679.66   505.4  680.09   529.2  680.98
#Mann= 6 ,-1 , 0
       0     .06       0    5.44     .12       0  125.31     .06       0
  133.33     .12       0   330.3    .045       0   350.2     .12       0
Bank Sta=330.3,350.2
XS Rating Curve= 0 ,0
Exp/Cntr=0.3,0.1

Type RM Length L Ch R = 1 ,1980.4  ,375,391.9,408.2
XS GIS Cut Line= 2
     2363863.071      317335.702      2364241.76      317017.777
#Sta/Elev= 30
       0   676.9      16  675.26    31.9  672.74    47.8  670.92    59.8  669.92
    71.8  669.34    91.7  667.85   103.7  666.66   147.5  664.23   167.5  664.13
   179.4  663.61   199.4   664.3  205.12664.0609   215.3     663   223.3  662.67
   231.3  663.02   247.2  664.44   255.2  664.27   263.2  664.67   271.2  664.64
     315  665.96     323  666.42     331  667.47   342.9  668.18   370.8  669.09
   382.8  669.72   394.8  670.84   418.7  671.27   438.6  672.74   494.4  675.61
#Mann= 4 ,-1 , 0
       0     .06       0  205.12     .12       0   215.3    .045       0
   231.3     .12       0
Bank Sta=215.3,231.3
XS Rating Curve= 0 ,0
Exp/Cntr=0.3,0.1

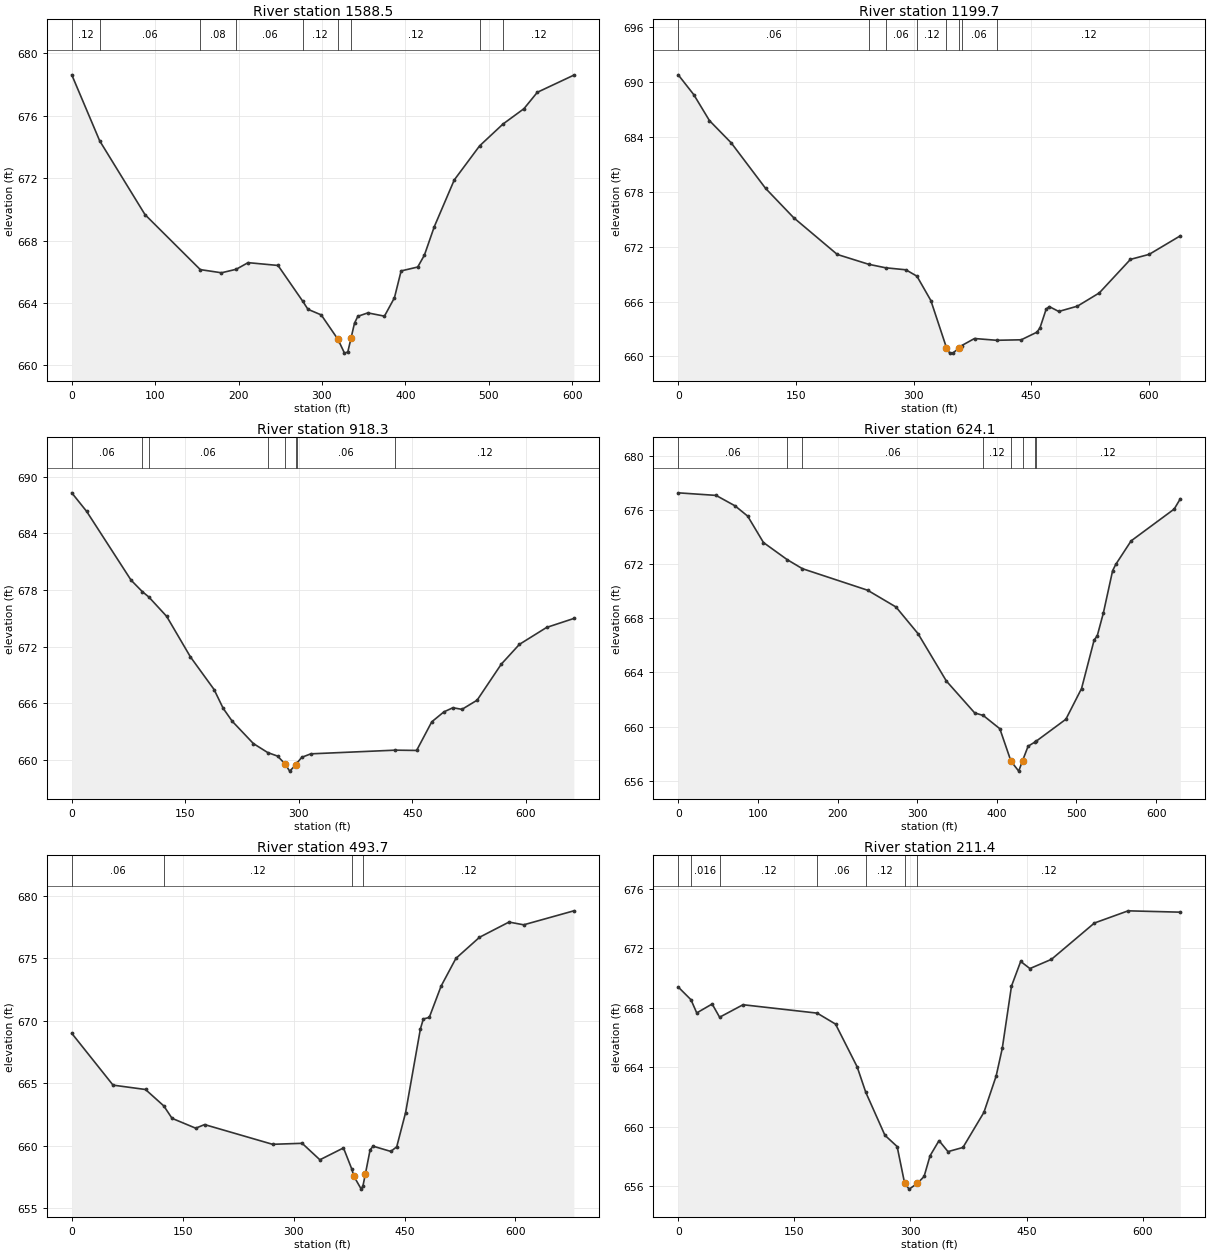
Type RM Length L Ch R = 1 ,1588.5  ,389.2,388.8,387.8
XS GIS Cut Line= 3
     2363928.175      317491.952     2364370.884      317488.697
     2364510.858      317564.652
#Sta/Elev= 30
       0  678.63   33.48674.3986    87.8  669.67   154.1666.1437   179.5  665.94
  197.15 666.165   211.4  666.59   247.3  666.41  276.75664.1311   283.2   663.6
   299.1  663.24   319.1  661.68     327  660.79     331  660.87     335  661.79
     339  662.71     343  663.15     355  663.37   374.9  663.16   386.9  664.34
   394.9  666.06   414.8  666.31   422.8  667.07   434.7   668.9   458.6  671.89
  489.01674.0768  517.09675.4771   542.2  676.46   558.2  677.51     602  678.61
#Mann= 9 ,-1 , 0
       0     .12       0   33.48     .06       0   154.1     .08       0
  197.15     .06       0  276.75     .12       0   319.1    .045       0
     335     .12       0  489.01     .06       0  517.09     .12       0
Bank Sta=319.1,335
XS Rating Curve= 0 ,0
Exp/Cntr=0.3,0.1

Type RM Length L Ch R = 1 ,1199.7  ,280.8,281.4,281.8
XS GIS Cut Line= 2
     2363877.177      317871.726     2364517.368      317863.046
#Sta/Elev= 30
       0  690.82    19.9  688.64    39.8  685.81    67.6  683.37   111.4  678.39
   147.1  675.19   202.8  671.16  242.76 670.086  264.46   669.7   290.3  669.48
  304.36668.7818   322.1  666.12     342  660.96     346  660.38     350  660.36
   357.9   660.9  361.56661.1927   377.8  661.96  405.91661.7654   437.4  661.82
   457.3  662.65   461.3  663.13   469.2  665.19   473.2  665.45   485.2  664.92
     509   665.5   536.9  666.95   576.6  670.62   600.5  671.17   640.2   673.2
#Mann= 8 ,-1 , 0
       0     .06       0  242.76     .08       0  264.46     .06       0
  304.36     .12       0     342    .045       0   357.9     .12       0
  361.56     .06       0  405.91     .12       0
Bank Sta=342,357.9
XS Rating Curve= 0 ,0
Exp/Cntr=0.3,0.1

Type RM Length L Ch R = 1 ,918.3   ,305.3,294.2,282.4
XS GIS Cut Line= 3
     2363879.347      318027.976     2364043.193      318120.207
     2364518.453      318122.377
#Sta/Elev= 30
       0  688.28    19.6  686.32    78.3  679.04   93.16677.8239  101.63677.2665
   125.4   675.2   156.7  670.92     188  667.46     200  665.47     212   664.1
   239.9  661.74  258.85660.7867   271.9  660.41  281.64659.5947   287.9  658.82
   295.8  659.47  297.39659.6588   303.8  660.28   315.8  660.65  427.48  661.04
   455.6  661.01   475.6  664.04   491.6  665.09   503.5  665.53   515.5  665.36
   535.5  666.33   567.4  670.14   591.4  672.24   627.3  674.03   663.3  674.98
#Mann= 8 ,-1 , 0
       0     .06       0   93.16     .08       0  101.63     .06       0
  258.85     .12       0  281.64    .045       0   295.8     .12       0
  297.39     .06       0  427.48     .12       0
Bank Sta=281.64,295.8
XS Rating Curve= 0 ,0
Exp/Cntr=0.3,0.1

Type RM Length L Ch R = 1 ,624.1   ,122,130.4,139
XS GIS Cut Line= 4
     2363948.792      318224.374      2364241.76       318390.39
     2364407.776      318299.244     2364511.943      318304.669
#Sta/Elev= 30
       0  677.26    47.5  677.07    71.3   676.3    87.2  675.54     107  673.59
  136.77672.3282  155.91671.6583   237.7  670.07   273.4  668.83   301.1  666.86
   336.7  663.36   372.2  661.01  382.97  660.82   403.8  659.84  417.76 657.446
   427.5  656.71  432.36657.4871   439.3  658.55  448.38658.8772  449.15 658.908
   486.7  660.54   506.4  662.81   522.2  666.39   526.1   666.7   533.8  668.39
   545.4  671.51   549.3  671.97   568.6  673.71   622.7  676.06   630.4  676.82
#Mann= 8 ,-1 , 0
       0     .06       0  136.77     .08       0  155.91     .06       0
  382.97     .12       0  417.76    .045       0  432.36     .12       0
  448.38     .06       0  449.15     .12       0
Bank Sta=417.76,432.36
XS Rating Curve= 0 ,0
Exp/Cntr=0.3,0.1

Type RM Length L Ch R = 1 ,493.7   ,282.5,282.3,280.8
XS GIS Cut Line= 4
     2364016.807      318392.665     2364103.613      318496.832
     2364520.623      318448.983     2364607.429      318361.093
#Sta/Elev= 30
       0  668.99    55.8  664.84    99.7  664.49  124.45663.1735   135.6  662.18
   167.6  661.39   179.6  661.68   271.5   660.1   311.5  660.18   335.5  658.86
   367.4  659.81   378.7  658.11  381.46  657.54   391.4  656.51   393.7  656.76
  396.89  657.69   403.4  659.65   407.4  659.95   431.4  659.53   439.4   659.9
   451.4  662.64   471.4  669.34   475.4  670.14   483.4  670.26   499.4  672.77
   519.4  674.99   551.3  676.68   591.2   677.9   611.1  677.68   678.9   678.8
#Mann= 4 ,-1 , 0
       0     .06       0  124.45     .12       0   378.7    .045       0
   393.7     .12       0
Bank Sta=381.46,396.89
XS Rating Curve= 0 ,0
Exp/Cntr=0.3,0.1

Type RM Length L Ch R = 1 ,211.4   ,203.3,211.4,219.9
XS GIS Cut Line= 5
      2364055.87       318676.52     2364334.512      318663.473
     2364376.685      318658.268     2364448.654      318629.956
     2364698.231       318618.36
#Sta/Elev= 30
       0   669.4   16.48668.5453    23.9  667.66    43.8  668.26   53.46667.3708
    83.7  668.21   179.5 667.646   203.2  666.91   231.1  664.04  242.27 662.327
     267  659.44   282.8  658.68  292.48  656.21   298.3  655.82  308.76   656.2
   317.6  656.67   325.3  658.06   336.9  659.08   348.5  658.34   367.8  658.62
   394.9  660.98   410.7  663.42   418.6  665.28   430.5  669.46   442.4  671.12
   454.3  670.64   482.1  671.26   537.6   673.7   581.2  674.52   648.6  674.43
#Mann= 7 ,-1 , 0
       0     .12       0   16.48    .016       0   53.46     .12       0
   179.5     .06       0  242.27     .12       0  292.48    .045       0
  308.76     .12       0
Bank Sta=292.48,308.76
XS Rating Curve= 0 ,0
Exp/Cntr=0.3,0.1
LCMann Table=0

Chan Stop Cuts=-1
Use User Specified Reach Order=0
Composite Channel Slope=5